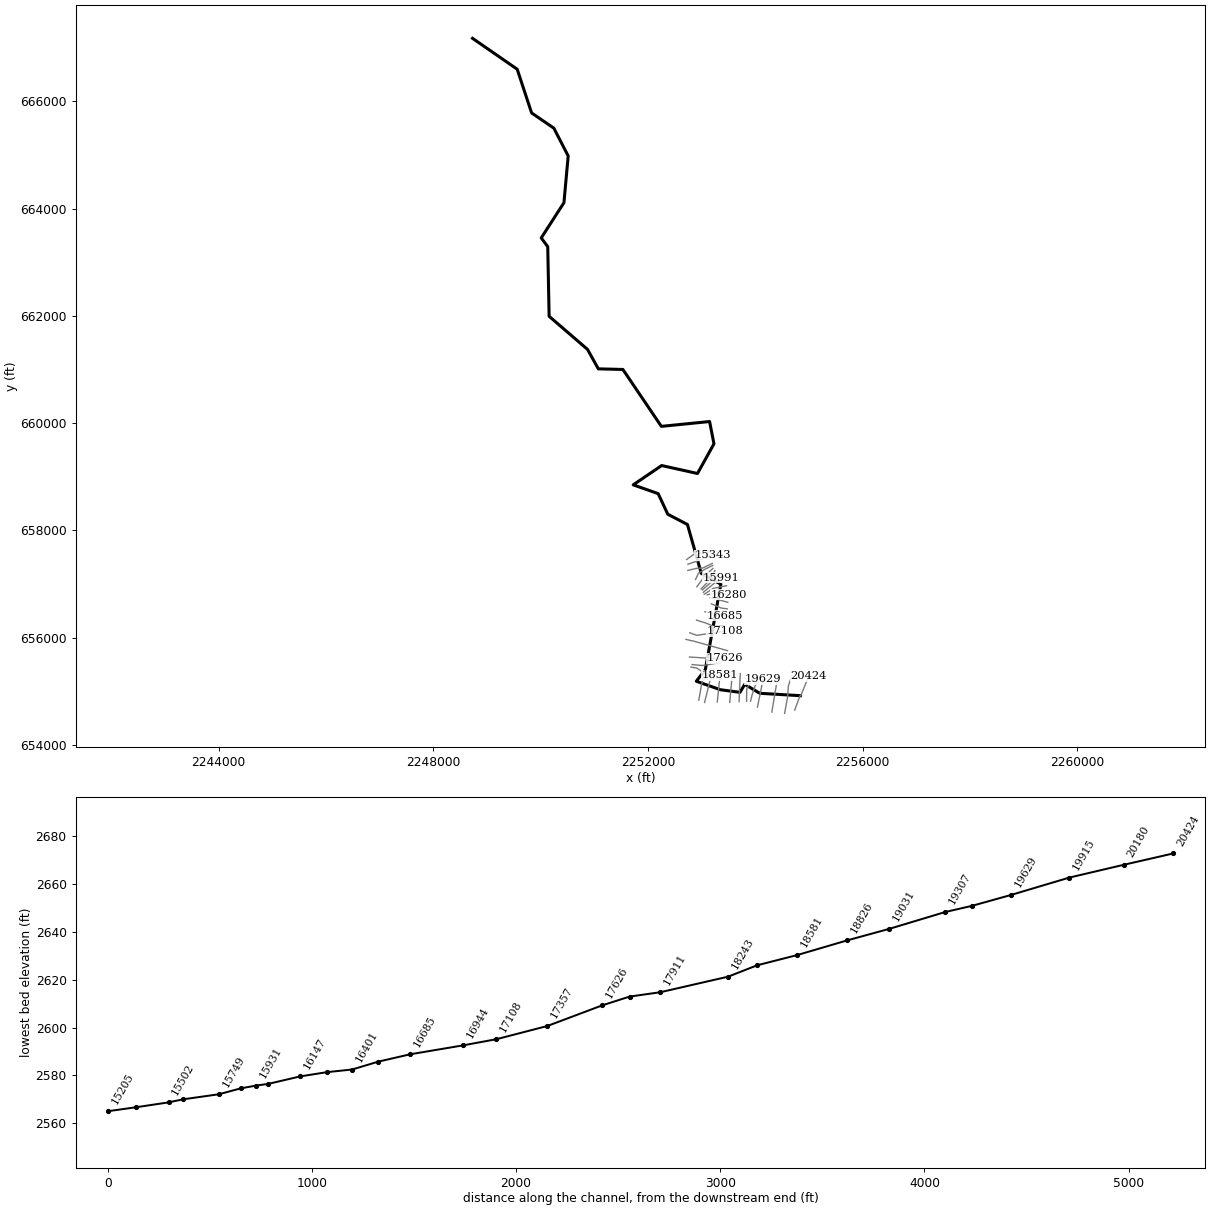
--- PANTHRN.prj (project) ---

Proj Title=PANTHRN
Current Plan=p01
Default Exp/Contr=0,0
English Units
Geom File=g01
Flow File=f01
Plan File=p01
Background Map Layer=Inundation Boundary (P100yr Value_0)
BEGIN DESCRIPTION:
----------MODEL BY WOOD PLC 2022----------
AFH study
Randolph County, WV
HEC-RAS Version: RAS 6.2
Vertical Datum: NAVD88
Projection: NAD 1983 StatePlane West Virginia S FIPS 4702 (US Feet)
Terrain: 1-meter LIDAR (FEMA Region III 3DEP collected 2016-2018)
Land Use: 2019 NLCD
Hydrologic Method:
WV SIR2010-5033 regression equations
Additional Model Notes:
KWSEL tie-in due to name change with CASSITYFK_DS. Used shared XS with both CASSITYFK_DS and CASSITYFK_US for name change and coincident peak, respectively.
END DESCRIPTION:
DSS Export Rating Curves= 0
DSS Export Rating Curve Sorted= 0
DSS Export Volume Flow Curves= 0
DXF OffsetX= 0
DXF OffsetY= 0
DXF ScaleX= 0
DXF ScaleY= 0

--- PANTHRN.p01 (plan) ---

Plan Title=Floodplain
Program Version=6.20
Short Identifier=Floodplain
Geom File=g01
Flow File=f01
Subcritical Flow
K Sum by GR= 0
Std Step Tol= 0.01
Critical Tol= 0.01
Num of Std Step Trials= 20
Max Error Tol= 0.3
Flow Tol Ratio= 0.001
Split Flow NTrial= 30
Split Flow Tol= 0.02
Split Flow Ratio= 0.02
Log Output Level= 0
Friction Slope Method= 1
Unsteady Friction Slope Method= 2
Unsteady Bridges Friction Slope Method= 1
Parabolic Critical Depth
Global Vel Dist= 0 , 0 , 0
Global Log Level= 0
CheckData=False
Encroach Param=-1 ,0,0, 0
Mapping Interval=1HOUR
Computation Time Step Use Courant=        0
Computation Time Step Use Time Series=    0
Computation Time Step Count To Double=0
Computation Time Step Max Doubling=0
Computation Time Step Max Halving=0
Computation Time Step Residence Courant=0
Run HTab= 0
Run UNet= 0
Run Sediment= 0
Run PostProcess= 0
Run WQNet= 0
Run RASMapper=-1
UNET Theta= 0
UNET Theta Warmup= 0
UNET ZTol= 0
UNET ZSATol= 0
UNET MxIter= 0
UNET Max Iter WO Improvement= 0
UNET MaxInSteps= 0
UNET DtIC= 0
UNET DtMin= 0
UNET MaxCRTS= 0
UNET WFStab= 0
UNET SFStab= 0
UNET WFX= 1
UNET SFX= 1
UNET Gravity=32.174
UNET 1D Methodology=Finite Difference
UNET DSS MLevel= 1
UNET Pardiso=0
UNET DZMax Abort= 0
UNET Use Existing IB Tables= 0
UNET Froude Reduction=False
UNET Froude Limit= 0
UNET Froude Power= 0
UNET D1 Cores= 0
UNET WindReference=Eulerian
UNET WindDragFormulation=Hsu (1988)
UNET D2 Coriolis=0
UNET D2 Cores= 0
UNET D2 Theta= 1
UNET D2 Theta Warmup= 1
UNET D2 Z Tol= 0.01
UNET D2 Volume Tol= 0.01
UNET D2 Max Iterations= 20
UNET D2 Equation= 0
UNET D2 RampUpFraction=0.1
UNET D2 TimeSlices= 1
UNET D2 Turbulence Formulation=Non-Conservative (original)
UNET D2 Eddy Viscosity=0.3
UNET D2 Transverse Eddy Viscosity=0.1
UNET D2 Smagorinsky Mixing=0
UNET D2 BCVolumeCheck=0
UNET D2 Cores=0
UNET D2 SolverType=PARDISO (Direct)
UNET D2 Minimum Iterations= 2147483647
UNET D2 Maximum Iterations= 2147483647
UNET D2 Restart Number= 10
UNET D2 Relaxation Coeff=1.3
UNET D2 SOR Precondition Iterations= 10
UNET D2 ILUT Maximum Fill= 8
UNET D2 ILUT Tolerance=1E-08
UNET D1D2 MaxIter= 0
UNET D1D2 ZTol=0.01
UNET D1D2 QTol=0.1
UNET D1D2 MinQTol=1
Write IC File= 0
Write IC File at Fixed DateTime=0
Write IC File at Sim End=0
Echo Input=False
Echo Parameters=False
Echo Output=False
Write Detailed= 0
HDF Write Warmup=0
HDF Write Time Slices=0
HDF Flush=0
HDF Compression= 1
HDF Chunk Size= 1
HDF Spatial Parts= 1
HDF Use Max Rows=0
HDF Fixed Rows= 1
Calibration Method= 0
Calibration Iterations= 20
Calibration Max Change=0.05
Calibration Tolerance=0.2
Calibration Maximum=1.5
Calibration Minimum=0.5
Calibration Optimization Method= 1
WQ AD Non Conservative
WQ ULTIMATE=-1
WQ Max Comp Step=1HOUR
WQ Output Interval=15MIN
WQ Output Selected Increments= 0
WQ Output face flow=0
WQ Output face velocity=0
WQ Output face area=0
WQ Output face dispersion=0
WQ Output cell volume=0
WQ Output cell surface area=0
WQ Output cell continuity=0
WQ Output cumulative cell continuity=0
WQ Output face conc=0
WQ Output face dconc_dx=0
WQ Output face courant=0
WQ Output face peclet=0
WQ Output face adv mass=0
WQ Output face disp mass=0
WQ Output cell mass=0
WQ Output cell source sink temp=0
WQ Output nsm pathways=0
WQ Output nsm derived pathways=0
WQ Create Restart=0
WQ Fixed Restart=0
WQ System Summary=0
WQ Write To DSS=0
Sorting and Armoring Iterations= 10
XS Update Threshold= 0.02
Bed Roughness Predictor= 0
Hydraulics Update Threshold= 0.02
Energy Slope Method= 1
Volume Change Method= 1
Sediment Retention Method= 0
Sediment TS Multiplier= 1
Warm Up Method= 0
XS Weighting Method= 0
Number of US Weighted Cross Sections= 1
Number of DS Weighted Cross Sections= 1
Upstream XS Weight=0
Main XS Weight=1
Downstream XS Weight=0
Number of DS XS's Weighted with US Boundary= 1
Upstream Boundary Weight= 1
Weight of XSs Associated with US Boundary= 0
Number of US XS's Weighted with DS Boundary= 1
Downstream Boundary Weight= 0.5
Weight of XSs Associated with DS Boundary= 0.5
Percentile Method= 0
Sediment Output Level= 3
Mass or Volume Output= 0
Output Increment Type= 1
Profile and TS Output Increment= 1
Transport Output Increment 1
XS Output Flag= 0
XS Output Increment= 10
Read HDF5 Sediment Hotstart= 0
Sediment Hotstart Type= 0
Write Gradation File= 0
Read Gradation Hotstart= 0
Write HDF5 File= 1
Write Binary Output= 1
Write DSS Sediment File= 0
DSS Sediment Output Type= 1
SV Curve= 0
Specific Gage Flag= 0
Subcell Erosion Methods= 0
Subcell Deposition Methods= 0
Advection Scheme= 1
Matrix Solver= 0
Implicit Weighting Factor= 1
Maximum Outer Loop Convergence Iterations= 5
Convergence Maximum Absolute= 0.001
Convergence RMSE= 0.0001
Grain Fractions Max Abs Error= 0.001
Max Subgrid Regions= 1
Max Subgrid Length Scale= 3.402823E+38
Initial Layer Thickness= 3.402823E+38
Min Layer Thickness= 3.402823E+38
Max Layer Thickness= 3.402823E+38
Number of Layers= 5

--- PANTHRN.f01 (steady flow) ---

Flow Title=Flow
Program Version=6.20
Number of Profiles= 1
Profile Names=P100yr
River Rch & RM=PANTHRN,Main            ,20424
     386
River Rch & RM=PANTHRN,Main            ,15205
     439
River Rch & RM=PANTHRN,Main            ,14982
     550
River Rch & RM=PANTHRN,Main            ,14358
     612
River Rch & RM=PANTHRN,Main            ,10724
     784
River Rch & RM=PANTHRN,Main            ,7759
     883
River Rch & RM=PANTHRN,Main            ,3500
    1710
River Rch & RM=PANTHRN,Main            ,1
    2720
Boundary for River Rch & Prof#=PANTHRN,Main            , 1
Up Type= 0
Dn Type= 1
Dn Known WS=2099.7
DSS Import GetInterval= 0
DSS Import GetPeak= 0
DSS Import FillOption= 0

--- PANTHRN.g01 (geometry) ---

Geom Title=Geometry
Program Version=6.20

River Reach=PANTHRN         ,Main
Reach XY= 30
2254837.10299999      654919.5372254080.59133551654964.214980319
     2253801.332655131.6430000072253712.03399999654982.033000022
2253346.40899998655030.6440000092252898.84000003655188.629999995
2253066.20100003655404.472000018     2253356.139 656997.07600002
2252991.00000003657200.2339999972252733.45699999658110.645999998
2252366.91600004658302.0039999932252187.92000005658686.065000013
2251722.64600003658849.5360000132252253.16000003659209.538000003
2252920.69500001659061.307999998     2253227.361659614.028000012
2253146.07000002660029.912000015     2252247.234659939.888000011
2251530.76399998661000.4490000012251073.04700001661012.072000012
2250871.49049395661374.6460597222250156.23269118661991.774822697
2250130.35200003663289.6260000172250009.22000001663452.780000016
2250432.20755413664108.494987279  2250511.284288664981.052924439
2250244.32599999      665498.647      2249829.88665782.328999996
2249561.28600003 666597.711000012248728.96908394667173.162311268

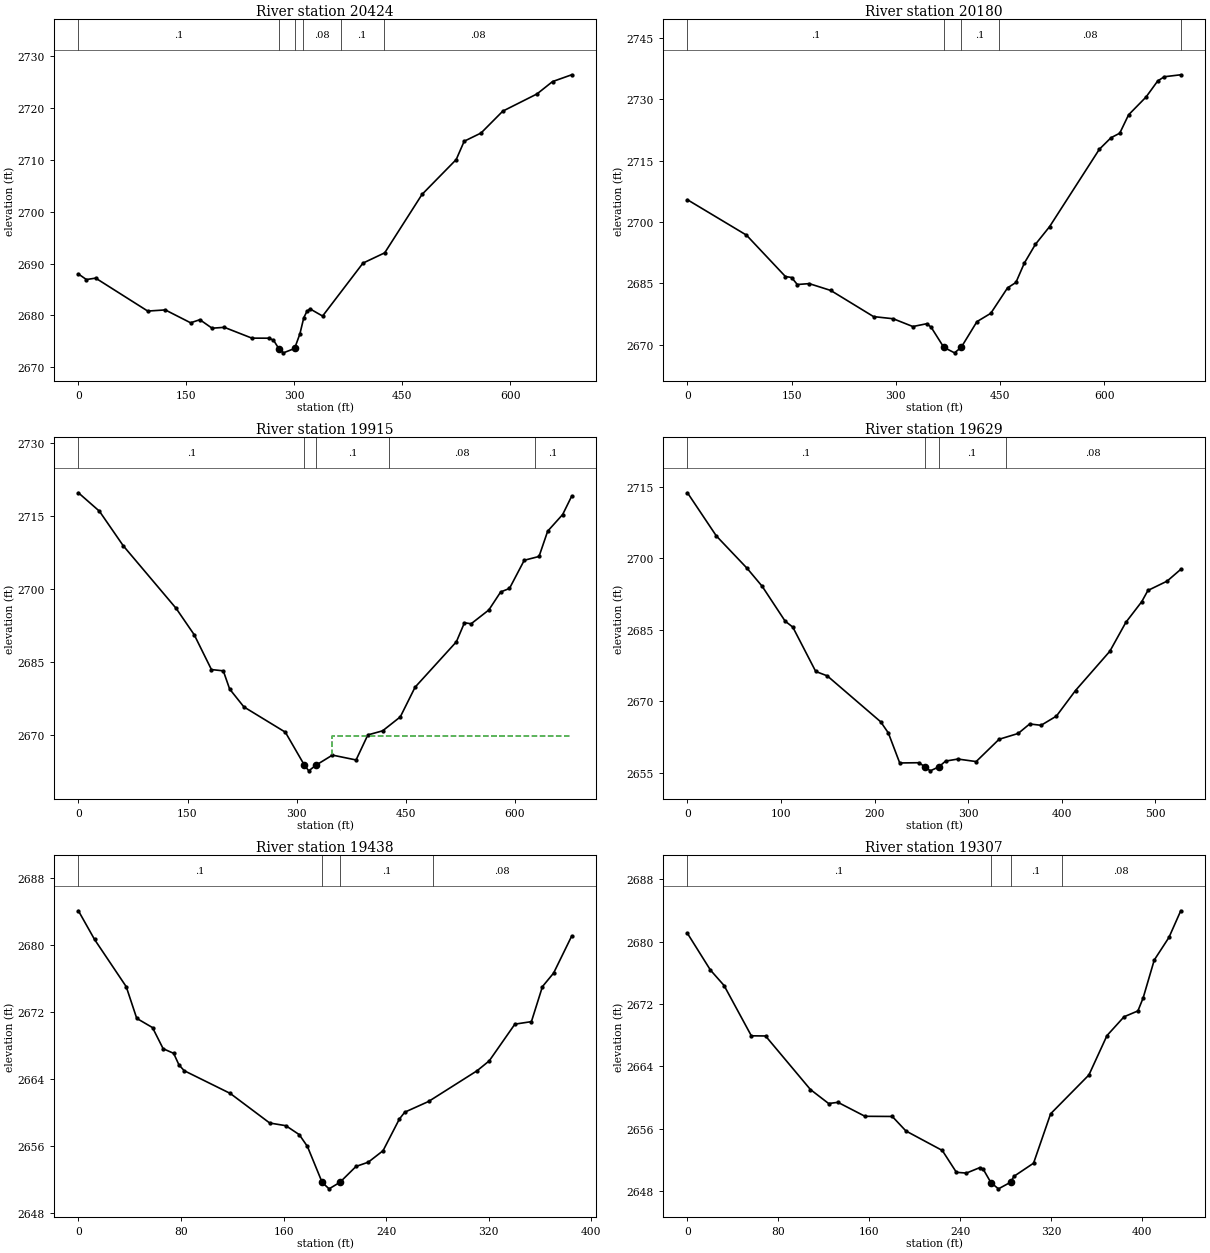
Type RM Length L Ch R = 1 ,20424   ,235.9,244,250.5
XS GIS Cut Line= 4
2254731.79126306654650.7694927312254825.23019282  654906.5063151
2254852.90033549654938.0617503032254992.26171639655281.861304219
#Sta/Elev= 30
       0 2687.99    11.1 2686.92      24 2687.19    96.3 2680.85   120.7 2681.07
   155.9 2678.59   168.7 2679.19   185.7 2677.55   202.7 2677.72     241 2675.64
   264.2 2675.63   270.9 2675.27   278.42673.627   284.8 2672.81   300.32673.647
   307.7 2676.47   313.1 2679.58   317.6 2680.84   321.9 2681.26   339.2 2679.89
   395.3 2690.08   425.5 2692.06   477.3  2703.3   524.8 2710.01   535.9 2713.54
   559.3 2715.12   589.5 2719.33     637 2722.64   658.6 2725.02   685.2 2726.33
#Mann= 6 ,-1,0
       0      .1       0   278.4    .045       0   300.3      .1       0
  312.27     .08       0  364.24      .1       0  424.24     .08       0
Bank Sta=278.4,300.3
XS Rating Curve= 0 ,0
Exp/Cntr=0.3,0.1

Type RM Length L Ch R = 1 ,20180   ,263,265.7,264.5
XS GIS Cut Line= 4
2254543.74616057654589.6537546462254599.05941972654893.016417558
2254613.47995236655098.3373347342254674.57454623 655284.61413931
#Sta/Elev= 30
       0 2705.46    84.9 2696.82     141  2686.7     150 2686.45   158.1 2684.74
   175.3 2684.96   206.3 2683.29   267.9  2676.9   296.3 2676.37   324.5 2674.47
   344.6 2675.16   350.8 2674.31   369.1 2669.38   384.5 2668.04   394.1 2669.37
   416.8 2675.67   436.7  2677.7   460.9 2683.93   472.9 2685.24     485 2689.97
     501 2694.57   521.4 2698.89     593  2717.8   609.8 2720.62   622.4 2721.73
   635.1 2726.22   660.3 2730.58   677.1 2734.51   686.6 2735.53   710.2 2736.01
#Mann= 5 ,-1,0
       0      .1       0   369.1    .045       0   394.1      .1       0
  448.36     .08       0  710.23     .05       0
Bank Sta=369.1,394.1
XS Rating Curve= 0 ,0
Exp/Cntr(USF)=0,0
Exp/Cntr=0.3,0.1

Type RM Length L Ch R = 1 ,19915   ,285,285.3,284.4
XS GIS Cut Line= 3
2254305.72456917654612.677980294      2254357.29      654925.534
2254417.96778663655281.442538074
#Sta/Elev= 30
       0 2719.77    28.9 2715.99    61.7 2708.89   134.3 2696.06   159.2 2690.64
   182.9 2683.49   199.2 2683.23   207.9  2679.5   227.5 2675.83   284.5 2670.64
   310.72663.874   316.7 2662.71   326.62663.873   349.2 2665.94   381.7 2664.94
   397.9 2670.08   418.2 2670.92   442.5 2673.78   462.8 2679.87   519.6 2689.19
   530.7  2693.1   539.9 2692.89   564.2 2695.72   580.5 2699.42   592.6 2700.14
   612.9 2705.92   633.2  2706.7   645.1 2711.89   665.7 2715.31   678.1 2719.07
#Mann= 5 ,-1,0
       0      .1       0   310.7    .045       0   326.6      .1       0
  427.08     .08       0  627.08      .1       0
#XS Ineff= 2 , 0
                          348.62         2669.87
Permanent Ineff=
       F       F
Bank Sta=310.7,326.6
XS Rating Curve= 0 ,0
Exp/Cntr=0.3,0.1

Type RM Length L Ch R = 1 ,19629   ,190.1,191.5,188.3
XS GIS Cut Line= 2
2254037.17548138654706.8776425632254143.23125057655223.422647871
#Sta/Elev= 30
       0  2713.7    30.9 2704.65    63.6 2697.91    79.9  2694.1   104.4 2686.81
   112.6 2685.56   137.1 2676.27   149.4 2675.35   206.5 2665.73   214.7  2663.4
   226.9  2657.1   247.4 2657.15   253.92656.286   259.6 2655.45   268.82656.298
   275.9 2657.49   289.1 2657.92   308.6 2657.39   333.1 2662.06   353.5 2663.28
   365.8 2665.27     378 2664.99   394.4 2666.92   414.8 2672.28   451.5  2680.5
   468.6 2686.55   485.6 2690.89   492.2 2693.24   512.7 2695.19   527.3 2697.66
#Mann= 4 ,-1,0
       0      .1       0   253.9    .045       0   268.8      .1       0
     340     .08       0
Bank Sta=253.9,268.8
XS Rating Curve= 0 ,0
Exp/Cntr(USF)=0,0
Exp/Cntr=0.3,0.1

Type RM Length L Ch R = 1 ,19438   ,132,131.2,130.2
XS GIS Cut Line= 4
2253909.22902979 654816.968506872253936.45808004654929.053894695
2253980.69482043655063.0703064682254027.79303927  655182.3857942
#Sta/Elev= 30
       0 2684.05    12.6 2680.63    37.3    2675    45.5 2671.22    57.8 2670.12
    66.1  2667.6    74.3 2667.05    78.4 2665.68    82.5 2664.98   118.4 2662.27
   149.2 2658.74   161.8 2658.42   172.2 2657.36   178.6 2655.95   190.12651.659
   195.5 2650.89   203.9 2651.66   216.5 2653.56   226.1 2654.07   237.6 2655.44
   250.3 2659.21   254.5 2660.03   273.1 2661.31   310.9 2664.97   320.4 2666.15
   340.4 2670.53   353.3 2670.83   361.9 2675.01   370.6 2676.62   384.7 2681.03
#Mann= 4 ,-1,0
       0      .1       0   190.1    .045       0   203.9      .1       0
  276.47     .08       0
Bank Sta=190.1,203.9
XS Rating Curve= 0 ,0
Exp/Cntr(USF)=0,0
Exp/Cntr=0.3,0.1

Type RM Length L Ch R = 1 ,19307   ,271.9,275.3,279.7
XS GIS Cut Line= 3
2253835.01690143 654816.942226072253837.30690974655046.324273102
2253934.64322868655226.344131786
#Sta/Elev= 30
       0 2681.06    20.2 2676.36    32.2 2674.38    56.2 2667.93    68.7 2667.91
   108.2 2661.04   124.2 2659.25   132.4  2659.4   156.2 2657.61   180.2 2657.59
   192.2 2655.73   224.2 2653.23   236.6 2650.43   245.4 2650.33   257.2 2651.03
   260.2 2650.83     2672649.104   273.6 2648.31   284.32649.156   287.2 2649.91
   304.5  2651.6   319.5 2657.93   353.2 2662.91   369.1 2667.96   384.1 2670.37
   396.3 2671.12   400.9 2672.78   410.7 2677.65   423.6 2680.54     434 2683.96
#Mann= 4 ,-1,0
       0      .1       0     267    .045       0   284.3      .1       0
  329.39     .08       0
Bank Sta=267,284.3
XS Rating Curve= 0 ,0
Exp/Cntr=0.3,0.1

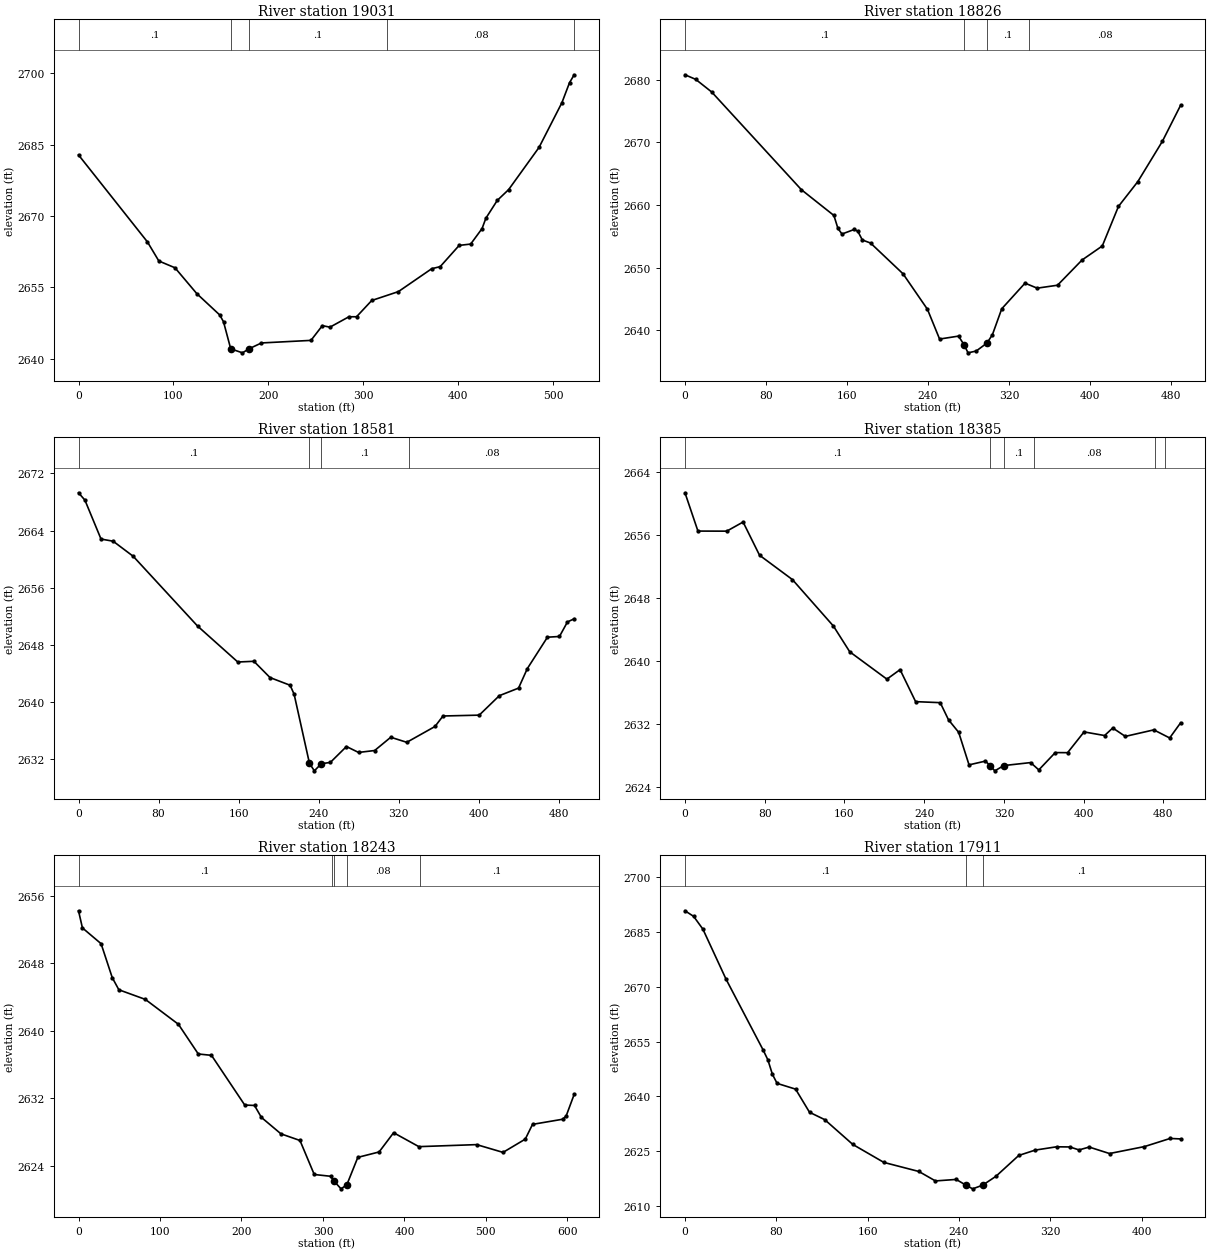
Type RM Length L Ch R = 1 ,19031   ,204.2,205.7,206.6
XS GIS Cut Line= 3
2253696.06361361654808.5965917922253700.94624329654963.769702797
2253718.39002805655330.089182666
#Sta/Elev= 30
       0 2682.87    72.6 2664.57    84.6 2660.56   101.6 2659.13   124.6 2653.69
   148.7 2649.21   152.7 2647.78   160.32642.084   172.7 2641.24   179.32642.067
   192.7 2643.32   244.8 2643.86   256.8 2646.96   264.8 2646.64   284.8 2648.83
   292.8 2648.83   308.8 2652.25   336.9 2654.12     372 2658.94   380.9 2659.37
   400.9 2663.84     413 2664.12     425 2667.38     429 2669.55     441  2673.3
     453 2675.58     485 2684.45   509.1 2693.86   517.1 2698.06     522 2699.73
#Mann= 5 ,-1,0
       0      .1       0   160.3    .045       0   179.3      .1       0
  325.25     .08       0  521.98     .05       0
Bank Sta=160.3,179.3
XS Rating Curve= 0 ,0
Exp/Cntr(USF)=0,0
Exp/Cntr=0.3,0.1

Type RM Length L Ch R = 1 ,18826   ,242.5,244.6,245.5
XS GIS Cut Line= 2
2253521.62576605654794.6415639872253564.96477823655282.363373365
#Sta/Elev= 30
       0  2680.8    10.6 2680.07    26.4 2678.05     115 2662.46   147.1 2658.35
   151.1 2656.28   155.1 2655.39   167.2 2656.12   170.7 2655.83   175.2 2654.44
   183.3 2653.95   215.4 2649.04   239.5 2643.38   251.5 2638.63   270.2  2639.1
   275.72637.711   279.6 2636.43   287.7 2636.72   298.32637.993   303.7 2639.33
   312.9 2643.46   335.9 2647.55   347.9 2646.75     368 2647.22   392.2 2651.24
   412.2 2653.48   428.2  2659.8   447.3 2663.75   471.6 2670.19   489.6 2675.94
#Mann= 4 ,-1,0
       0      .1       0   275.7    .045       0   298.3      .1       0
     340     .08       0
Bank Sta=275.7,298.3
XS Rating Curve= 0 ,0
Exp/Cntr=0.3,0.1

Type RM Length L Ch R = 1 ,18581   ,196.3,195.6,194.8
XS GIS Cut Line= 3
 2253289.0419693654802.7819968742253330.25525625 655200.11039214
2253336.78385566655295.808241334
#Sta/Elev= 30
       0 2669.29     6.4 2668.26    22.5  2662.8    34.6  2662.5    54.7 2660.38
     119  2650.6   159.2 2645.56   175.3 2645.66   191.4 2643.38   211.5  2642.3
   215.5 2641.04   230.82631.369   235.7  2630.3   242.72631.301   251.7 2631.48
   267.8 2633.71   279.9 2632.88     296 2633.15   312.1 2635.01   328.1  2634.3
   356.3 2636.52   364.3 2637.99   400.5 2638.11   420.6 2640.84   439.8  2641.9
   448.6 2644.64   468.7 2649.04   480.7 2649.14   488.7 2651.18   495.4 2651.62
#Mann= 4 ,-1,0
       0      .1       0   230.8    .045       0   242.7      .1       0
     330     .08       0
Bank Sta=230.8,242.7
XS Rating Curve= 0 ,0
Exp/Cntr(USF)=0,0
Exp/Cntr=0.3,0.1

Type RM Length L Ch R = 1 ,18385   ,141.5,142.2,142
XS GIS Cut Line= 3
2253052.32711895654792.550511621 2253155.9432004655211.201345774
2253214.55431718 655241.55353125
#Sta/Elev= 30
       0  2661.4      13 2656.53    41.9 2656.52    58.3 2657.68    74.8 2653.46
   107.8 2650.36     149 2644.44   165.3 2641.18   202.6  2637.7   215.8 2638.91
   231.4 2634.84   256.1 2634.71   264.4 2632.53   274.6 2630.94     285  2626.8
   301.5 2627.28   305.92626.715   310.9 2626.04   319.82626.709   346.8 2627.09
     355 2626.16   371.5 2628.36   383.9 2628.35   400.4 2630.99     421 2630.53
   429.2 2631.49   441.8 2630.42   470.4 2631.25   486.3 2630.22   497.3 2632.15
#Mann= 6 ,-1,0
       0      .1       0   305.9    .045       0   319.8      .1       0
     350     .08       0  471.28      .1       0  481.28     .08       0
Bank Sta=305.9,319.8
XS Rating Curve= 0 ,0
Exp/Cntr(USF)=0,0
Exp/Cntr=0.3,0.1

Type RM Length L Ch R = 1 ,18243   ,345.7,331.8,317.6
XS GIS Cut Line= 4
2252944.89398145654836.4232909922252991.99220029 655103.31319776
2253014.37795029655198.6264050022253199.81784201655350.077793909
#Sta/Elev= 30
       0 2654.23     4.8  2652.2    27.7 2650.33    41.4 2646.31    49.5 2644.87
      82 2643.73   122.6 2640.78     147 2637.26   163.2  2637.1     204 2631.21
     216 2631.16   224.4 2629.75   248.4  2627.8   271.8 2627.01   289.3 2622.98
   309.3 2622.77     314 2622.15   322.2 2621.28   329.3 2621.76   342.8 2625.01
   368.9 2625.65   386.7 2627.93   417.7 2626.28   488.6 2626.52     521  2625.6
   548.3 2627.17   557.2 2628.92   594.3 2629.53   598.5 2629.92   608.3 2632.47
#Mann= 5 ,-1,0
       0      .1       0  311.01     .08       0     314    .045       0
   329.3     .08       0  418.92      .1       0
Bank Sta=314,329.3
XS Rating Curve= 0 ,0
Exp/Cntr(USF)=0,0
Exp/Cntr=0.3,0.1

Type RM Length L Ch R = 1 ,17911   ,145.1,151.2,160.5
XS GIS Cut Line= 4
2252796.67259432655453.4483702412252907.79596388655434.066387179
2253093.86300127655308.7295633762253180.43585895655352.662058317
#Sta/Elev= 30
       0 2690.72     7.6 2689.19    15.7  2685.7      36 2672.02    68.5 2652.68
    72.6 2650.02    76.6 2646.05    80.7 2643.58    96.9 2642.01   109.1 2635.69
   122.4 2633.68     147 2626.91   174.2    2622   204.9 2619.52   219.4 2616.94
   237.6 2617.35   246.3 2615.75     252 2614.78   260.7 2615.77   272.4  2618.2
   292.4  2623.9   306.8 2625.36   325.5 2626.26   337.1 2626.22   345.2 2625.41
   354.1 2626.19   371.9 2624.42   402.5 2626.32     425 2628.54   434.2 2628.41
#Mann= 3 ,-1,0
       0      .1       0   246.3    .045       0   260.7      .1       0
Bank Sta=246.3,260.7
XS Rating Curve= 0 ,0
Exp/Cntr(USF)=0,0
Exp/Cntr=0.3,0.1

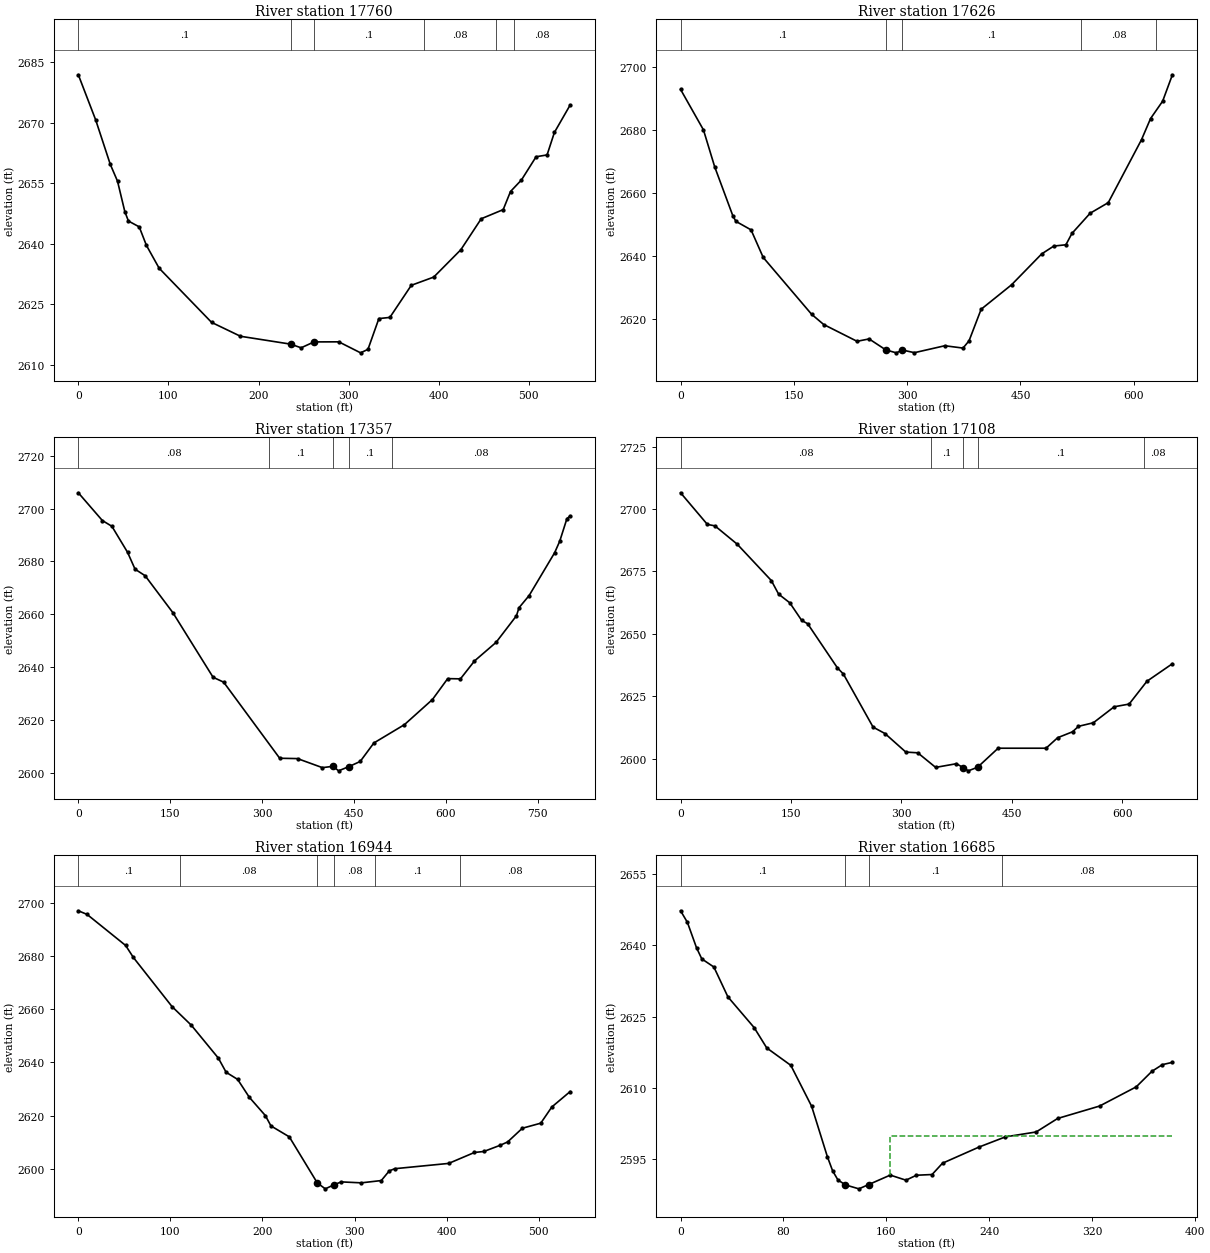
Type RM Length L Ch R = 1 ,17760   ,136.1,134.1,131.4
XS GIS Cut Line= 4
2252820.80057897655498.6019301162253012.96131184 655482.58853571
2253122.22917955655498.6019301162253361.48813127655539.106398319
#Sta/Elev= 30
       0 2681.94    19.3 2670.72    35.5  2659.7    43.5 2655.54    51.6    2648
    55.6 2645.65    67.6  2644.2    75.6  2639.6    89.7 2633.94   147.9  2620.5
     180 2617.05   235.62615.102   247.3 2614.19   261.62615.652   289.1 2615.67
   313.3 2612.94   321.5 2613.81   333.6 2621.44   345.8 2621.73   369.6  2629.7
   394.5 2631.74   424.6 2638.53   447.2 2646.21   471.6 2648.48   479.7 2652.97
   491.9 2655.85   508.1  2661.6   520.3 2662.05   528.4 2667.62   545.9 2674.43
#Mann= 6 ,-1,0
       0      .1       0   235.6    .045       0   261.6      .1       0
  383.26     .08       0  463.26      .1       0  483.26     .08       0
Bank Sta=235.6,261.6
XS Rating Curve= 0 ,0
Exp/Cntr(USF)=0,0
Exp/Cntr=0.3,0.1

Type RM Length L Ch R = 1 ,17626   ,269.9,269,265.2
XS GIS Cut Line= 3
2252771.01908194655640.0966223182253289.90961065655608.065107549
2253420.99115775655612.994966488
#Sta/Elev= 30
       0 2692.81    30.3 2679.97    45.2 2668.24    69.3 2652.67    73.3 2650.96
    93.3 2648.27   109.4 2639.52   173.5 2621.49   189.5 2618.25   233.6 2612.93
   249.6 2613.68   271.82610.185   285.7 2609.27   293.7 2610.16   309.6 2609.32
   349.8 2611.52   373.9 2610.78   381.9 2613.08   397.9 2623.09   438.1 2630.83
   478.1 2640.65   494.1 2643.13   510.1 2643.54   518.1 2647.13   542.2 2653.54
   566.2  2656.9   610.2 2676.86   622.2 2683.57   638.2 2689.08   651.1 2697.45
#Mann= 5 ,-1,0
       0      .1       0   271.8    .045       0   293.7      .1       0
  529.88     .08       0  629.88      .1       0
Bank Sta=271.8,293.7
XS Rating Curve= 0 ,0
Exp/Cntr=0.3,0.1

Type RM Length L Ch R = 1 ,17357   ,243,249.1,251.9
XS GIS Cut Line= 3
2252705.92274177655968.5416189772252862.91680457655932.491130482
 2253480.5632696655758.956008201
#Sta/Elev= 30
       0 2706.02    39.2 2695.51    54.8 2693.31    80.3 2683.48    92.6 2677.06
     109 2674.59   154.2 2660.62   219.9 2636.11   237.2 2634.24   328.6 2605.41
   357.7 2605.28   398.3 2601.85   415.8 2602.36   424.7 2600.64   441.82602.272
     460 2604.19   482.3  2611.2   532.2 2618.15   577.9 2627.67   602.8 2635.59
   623.6  2635.5   646.5 2642.28   681.7 2649.32     715 2659.42   719.1 2662.44
   735.7 2667.08   777.3  2683.3   785.6 2687.66   797.3 2696.19   802.6 2697.23
#Mann= 5 ,-1,0
       0     .08       0  311.08      .1       0   415.8    .045       0
   441.8      .1       0  511.08     .08       0
Bank Sta=415.8,441.8
XS Rating Curve= 0 ,0
Exp/Cntr=0.3,0.1

Type RM Length L Ch R = 1 ,17108   ,168.3,163.6,158.1
XS GIS Cut Line= 3
2252776.29312758656091.9818569172252907.95267557656044.131665644
2253430.33535437656122.113883626
#Sta/Elev= 30
       0  2706.5    36.4 2693.83    46.7 2693.25      77  2685.9   123.3 2671.35
   133.2 2665.92   148.4 2662.43   164.6 2655.37   172.7 2654.05   213.1 2636.38
   221.2 2633.92   261.6 2612.64   277.8 2610.06   306.1 2602.64   322.3 2602.35
   346.6 2596.51   374.9 2597.99     384 2596.41     391 2595.13   403.62596.574
   431.5 2604.19   496.6 2604.19   512.4  2608.4   532.6 2610.77   540.7 2612.96
   560.9 2614.38   589.2 2620.79   609.5 2621.87   633.7 2631.01   668.3 2638.03
#Mann= 5 ,-1,0
       0     .08       0  340.09      .1       0     384    .045       0
   403.6      .1       0  630.09     .08       0
Bank Sta=384,403.6
XS Rating Curve= 0 ,0
Exp/Cntr=0.3,0.1

Type RM Length L Ch R = 1 ,16944   ,255.6,259.1,258.7
XS GIS Cut Line= 4
2252903.08692349656327.9014462692253076.66204183656273.411559759
2253226.43437774656210.2999465122253416.06340854656211.609547895
#Sta/Elev= 30
       0 2696.97     9.5 2695.61    51.4 2683.94    59.8 2679.43   101.8 2660.98
   122.7    2654   152.1 2641.63   160.5 2636.33     173 2633.65   185.7 2626.93
   203.1 2620.07   209.2 2616.18   229.1 2612.08   259.5 2594.78   268.2 2592.55
   278.1 2594.15   285.6 2595.16   307.3  2594.8     329 2595.66   337.7  2599.3
   343.6 2600.11   402.2  2602.1   430.2 2606.21   440.4 2606.58   458.2 2608.92
   466.2 2610.16   482.2 2615.31   502.2 2617.21   514.2 2623.29   534.1 2629.08
#Mann= 6 ,-1,0
       0      .1       0     110     .08       0   259.5    .045       0
   278.1     .08       0  321.93      .1       0  414.45     .08       0
Bank Sta=259.5,278.1
XS Rating Curve= 0 ,0
Exp/Cntr(USF)=0,0
Exp/Cntr=0.3,0.1

Type RM Length L Ch R = 1 ,16685   ,156.7,155.5,152.3
XS GIS Cut Line= 2
2253059.94402028656483.0865239882253435.78780664656413.381160102
#Sta/Elev= 30
       0  2647.3     5.3 2644.87    12.4 2639.52    16.5 2637.18    25.9 2635.47
    36.8 2629.19    57.2 2622.73      67 2618.45    85.7 2614.79   101.9 2606.17
   114.1 2595.59   118.2  2592.6   122.3  2590.7   128.12589.653   138.6 2588.82
   146.22589.718     163 2591.71   175.2 2590.64   183.3 2591.68   195.5 2591.83
   203.6 2594.21   232.1 2597.62   252.5 2599.75   276.4 2600.78   293.1 2603.62
   325.7 2606.23   354.2 2610.27   366.4 2613.54   374.5 2614.94   382.3 2615.42
#Mann= 4 ,-1,0
       0      .1       0   128.1    .045       0   146.2      .1       0
     250     .08       0
#XS Ineff= 2 , 0
                             163            2600
Permanent Ineff=
       F       F
Bank Sta=128.1,146.2
XS Rating Curve= 0 ,0
Exp/Cntr(USF)=0,0
Exp/Cntr=0.3,0.1

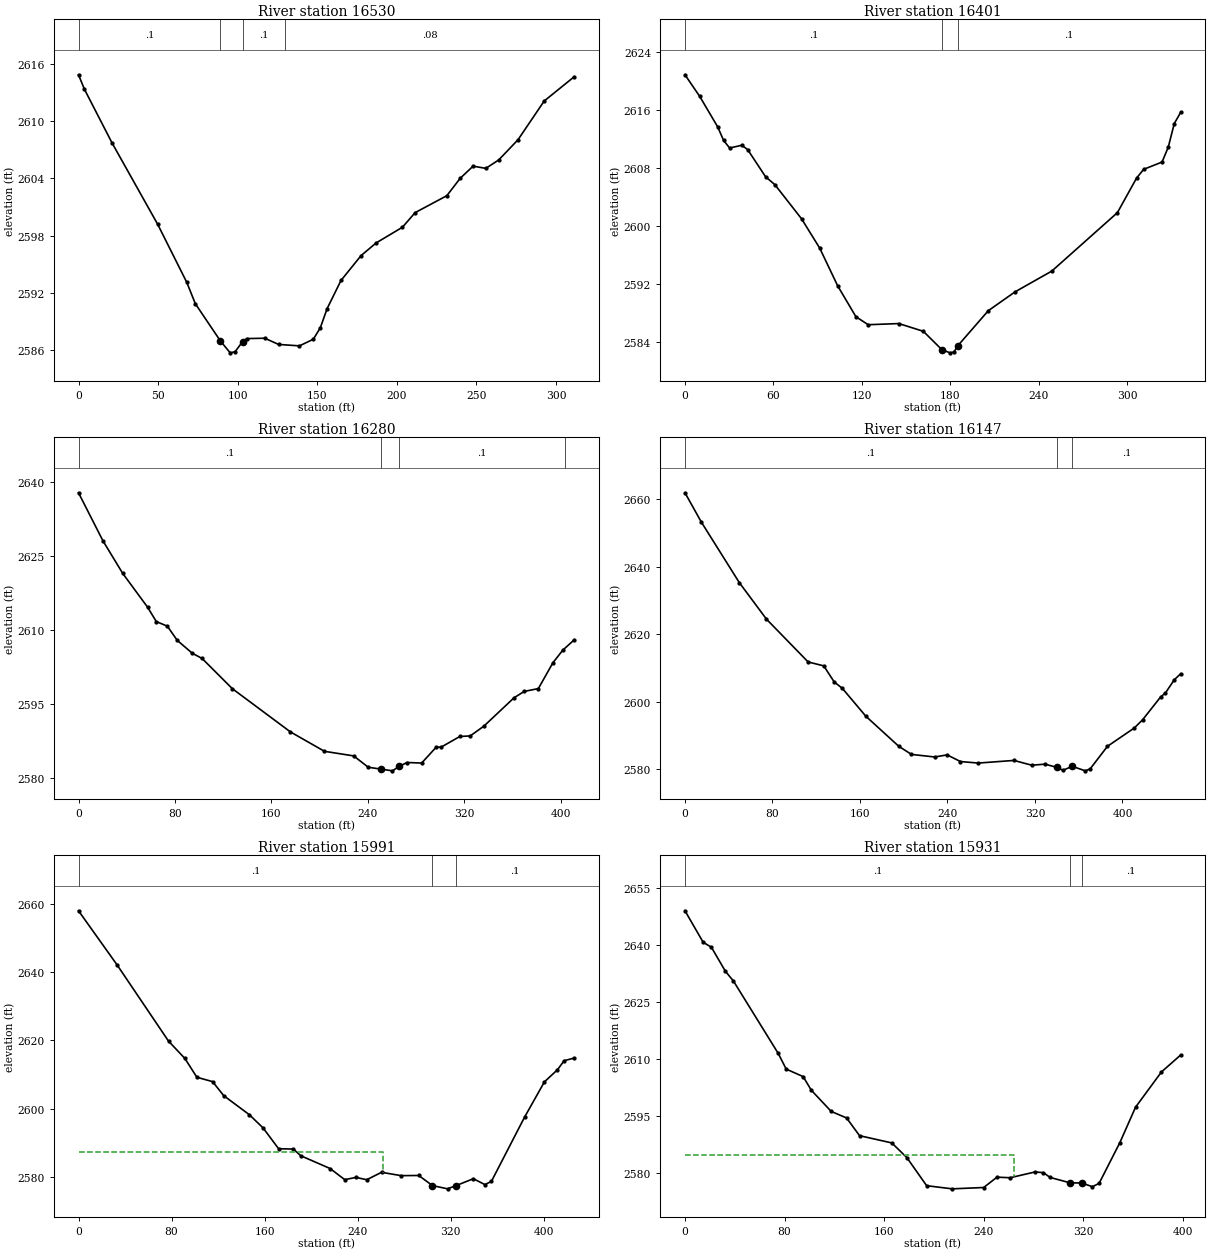
Type RM Length L Ch R = 1 ,16530   ,127.9,129.1,128.9
XS GIS Cut Line= 3
2253180.81335315656631.1660695332253359.78658474656553.715665216
2253475.15532384656538.319547188
#Sta/Elev= 30
       0 2614.84     3.7 2613.33    21.1  2607.7    49.7 2599.21      68 2593.13
    73.4 2590.89    89.2 2586.98    95.3 2585.75    98.4 2585.87   103.12586.931
   105.7 2587.24     117 2587.28   125.7 2586.63   138.8 2586.48   147.5 2587.17
   151.9 2588.36   156.2 2590.38   164.9 2593.32   177.5 2595.92     187 2597.25
   203.5 2598.89   211.5 2600.42   231.4 2602.19   239.8 2604.01   247.9 2605.28
   255.9 2605.05     264 2605.93   276.1 2608.04   292.6  2612.1   311.4 2614.63
#Mann= 4 ,-1,0
       0      .1       0    89.2    .045       0   103.1      .1       0
     130     .08       0
Bank Sta=89.2,103.1
XS Rating Curve= 0 ,0
Exp/Cntr(USF)=0,0
Exp/Cntr=0.3,0.1

Type RM Length L Ch R = 1 ,16401   ,119.4,120.8,121.3
XS GIS Cut Line= 3
2253158.37742315656742.2327457062253259.60956232 656723.32124718
2253484.32266245 656660.46832561
#Sta/Elev= 30
       0 2620.91      10 2617.92    22.2  2613.7    26.2 2611.83    30.3 2610.78
    38.5 2611.16    42.5 2610.57    54.7  2606.8      61 2605.71    79.1 2600.99
    91.4 2596.94   103.6 2591.72     116 2587.44   124.3 2586.34   145.1  2586.5
   161.7 2585.43   174.2 2582.91   179.8 2582.45   182.5 2582.56   185.2 2583.45
   205.8 2588.28     224 2590.89   248.9 2593.76   293.4 2601.84   306.4 2606.62
   311.2 2607.83   323.7 2608.84   327.9  2610.9     332 2614.17   336.3  2615.7
#Mann= 3 ,-1,0
       0      .1       0   174.2    .045       0   185.2      .1       0
Bank Sta=174.2,185.2
XS Rating Curve= 0 ,0
Exp/Cntr=0.3,0.1

Type RM Length L Ch R = 1 ,16280   ,129.8,132.7,134.3
XS GIS Cut Line= 4
2253100.46087846656799.3103894862253242.37723147656832.881999876
2253408.70930113  656813.04423012253505.60917658656800.073380631
#Sta/Elev= 30
       0 2637.77    20.3 2628.01    36.7 2621.41    57.3 2614.56    64.5 2611.66
    73.7 2610.71    81.9 2607.84    94.4 2605.22   102.5 2604.17   127.6 2598.04
   175.8 2589.27     204 2585.34   228.2 2584.41   240.3 2582.11   250.6 2581.74
   260.4 2581.38     266  2582.3   272.5 2583.07   284.6 2582.96   296.7 2586.19
   300.7 2586.18   316.3 2588.35   324.9 2588.46   336.2 2590.44   361.2 2596.19
   369.7 2597.49   381.4 2598.06   393.5 2603.31   401.7 2605.86   411.1 2607.94
#Mann= 4 ,-1,0
       0      .1       0   250.6    .045       0     266      .1       0
  403.34     .08       0
Bank Sta=250.6,266
XS Rating Curve= 0 ,0
Exp/Cntr(USF)=0,0
Exp/Cntr=0.3,0.1

Type RM Length L Ch R = 1 ,16147   ,151.6,156.6,156.1
XS GIS Cut Line= 3
2253045.65817111656810.9564937622253215.95454994656921.149858429
2253461.80725229 656968.24807727
#Sta/Elev= 30
       0 2661.86      15 2653.16    49.7 2635.27    74.5 2624.47   112.6  2611.8
   126.9 2610.64   136.4  2605.9     144 2603.95   165.4 2595.73   195.5 2586.84
   207.1 2584.44   228.3 2583.68   239.7  2584.3   251.9 2582.33   268.2 2581.88
   300.8 2582.66   317.1 2581.24   329.3 2581.56   340.2 2580.58   345.6 2579.76
   354.2 2580.91     366 2579.58   370.5 2580.17   386.3 2586.84   410.8 2592.25
   418.4 2594.68   434.8  2601.4   439.3 2602.63   447.4 2606.53   453.2 2608.29
#Mann= 3 ,-1,0
       0      .1       0   340.2    .045       0   354.2      .1       0
Bank Sta=340.2,354.2
XS Rating Curve= 0 ,0
Exp/Cntr(USF)=0,0
Exp/Cntr=0.3,0.1

Type RM Length L Ch R = 1 ,15991   ,60.4,59.9,58.6
XS GIS Cut Line= 2
2253029.37730533656848.1699012412253359.33475304657118.148176603
#Sta/Elev= 30
       0 2658.04    33.2 2642.15    77.4  2619.8    91.5  2614.7   101.8 2609.19
   115.3 2607.91   124.9 2603.79   146.9 2598.21   158.7 2594.34   172.1 2588.22
   184.8 2588.12   191.1 2586.17   216.4 2582.41     229 2579.14   238.6 2579.81
   247.9 2579.12   260.6  2581.3   277.5 2580.32   292.6 2580.37   304.42577.415
   317.4 2576.45   324.92577.423   339.6 2579.42   349.5  2577.7   355.1 2578.62
   383.6 2597.46   400.7 2607.83   411.9 2611.38   417.7 2614.06   426.3 2614.82
#Mann= 3 ,-1,0
       0      .1       0   304.4    .045       0   324.9      .1       0
#XS Ineff= 2 , 0
          262.01 2587.39
Permanent Ineff=
       F       F
Bank Sta=304.4,324.9
XS Rating Curve= 0 ,0
Exp/Cntr=0.3,0.1

Type RM Length L Ch R = 1 ,15931   ,70.1,75.1,76.4
XS GIS Cut Line= 3
 2253011.9450565656891.5256020912253235.75579243657088.207763971
2253305.27276344657160.268038798
#Sta/Elev= 30
       0 2649.12    14.6 2640.81    21.2  2639.5    32.5 2633.14    38.9 2630.59
    74.9 2611.48    81.3 2607.34    94.9 2605.36   101.5 2601.75   117.5 2596.16
   129.8 2594.45   140.2 2589.77   166.1 2587.86   178.2 2583.99   194.1 2576.57
   214.6 2575.74   239.9 2576.09   250.6 2578.82   261.2 2578.67   281.2  2580.2
   287.9 2580.01   293.3 2578.74  309.392577.324   318.7 2577.28   327.2 2576.31
   332.6 2577.17   349.3 2587.94   361.9 2597.29   382.7 2606.59   398.1 2611.05
#Mann= 3 ,0,0
       0      .1       0  309.39    .045       0   318.7      .1       0
#XS Ineff= 2 , 0
           264.1 2584.57
Permanent Ineff=
       F       F
Bank Sta=309.39,318.7
XS Rating Curve= 0 ,0
Exp/Cntr(USF)=0,0
Exp/Cntr=0.3,0.1

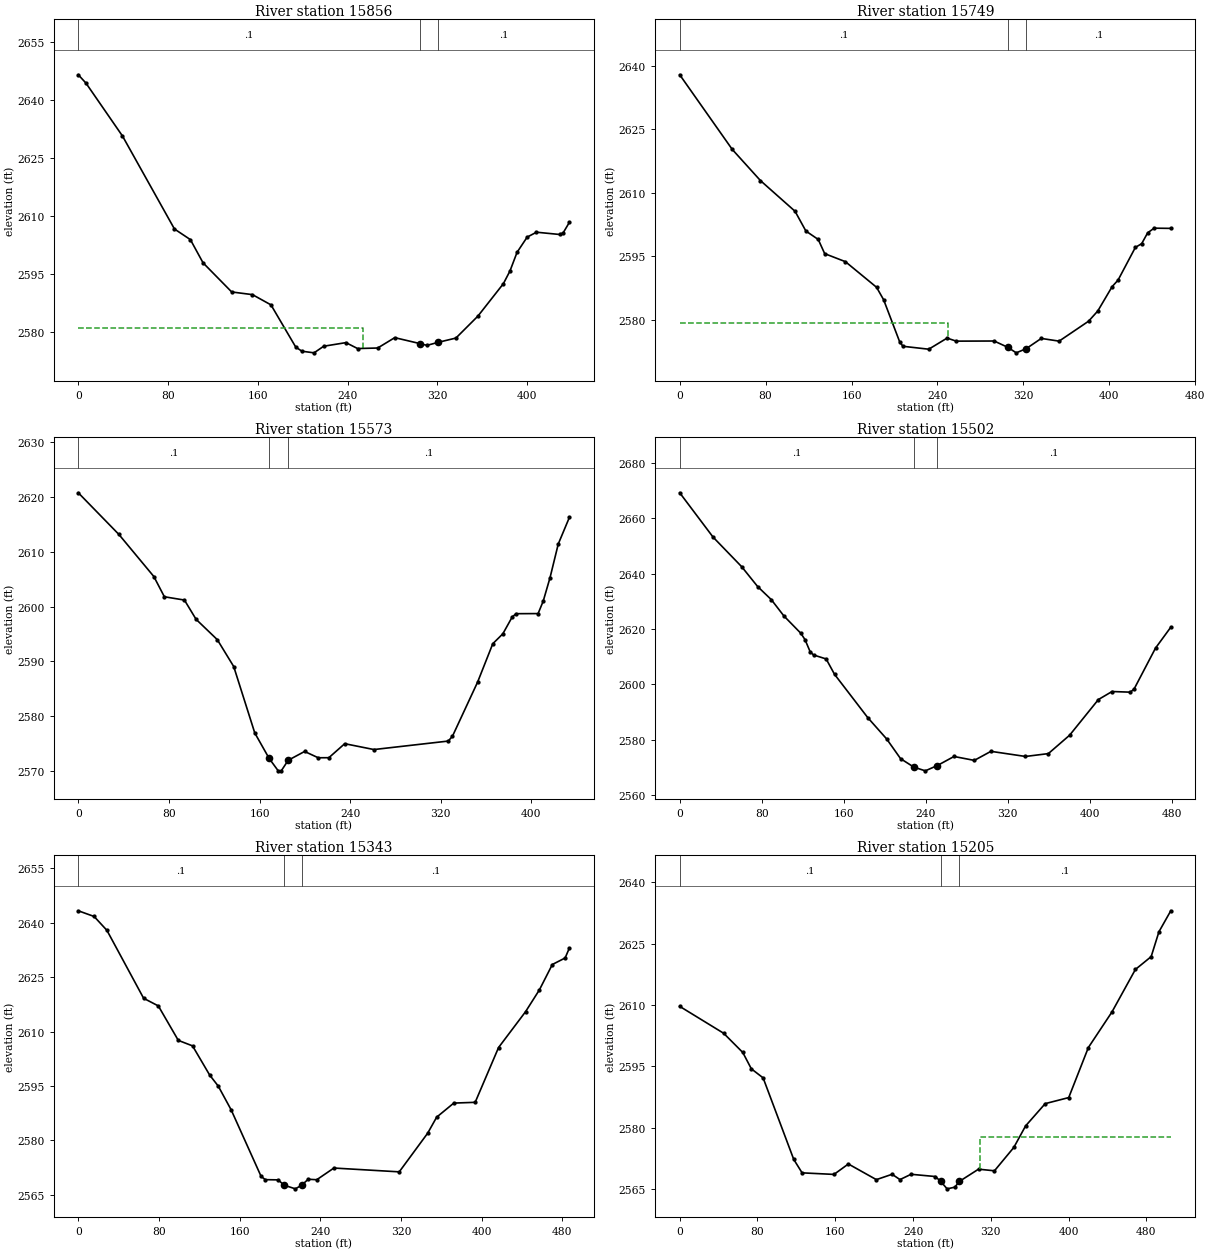
Type RM Length L Ch R = 1 ,15856   ,109.5,106.4,101.9
XS GIS Cut Line= 4
2252987.51222192656908.6416883952253178.76108652657110.078711523
2253196.61507932657160.8939217952253246.74359756 657254.28403797
#Sta/Elev= 30
       0 2646.51     6.8 2644.37    39.4 2630.66    85.7 2606.61    99.9 2603.86
   111.2 2597.85   136.7 2590.32   155.2 2589.63   171.7 2586.98   193.8 2576.05
   199.3 2574.99   210.1 2574.57   218.7 2576.28   238.5 2577.21   248.9 2575.68
   266.8 2575.82     282  2578.5   304.62576.954   310.7  2576.5   320.62577.284
   336.5 2578.39   356.1 2584.07   378.8 2592.46   384.7 2595.76     391 2600.58
     400 2604.51   408.3 2605.78     429 2605.19     432 2605.58   437.6 2608.32
#Mann= 3 ,-1,0
       0      .1       0   304.6    .045       0   320.6      .1       0
#XS Ineff= 2 , 0
             254 2580.95
Permanent Ineff=
       F       F
Bank Sta=304.6,320.6
XS Rating Curve= 0 ,0
Exp/Cntr(USF)=0,0
Exp/Cntr=0.3,0.1

Type RM Length L Ch R = 1 ,15749   ,175,175.8,168.5
XS GIS Cut Line= 3
2252908.02126877656948.8748727462253058.92396193657151.491410197
2253207.91916027657291.812591168
#Sta/Elev= 30
       0 2637.94    48.9 2620.28    75.2 2612.89   107.4 2605.63   117.5 2600.95
     129 2598.96     135  2595.6   154.3  2593.7   183.3 2587.64   189.9 2584.68
   204.9 2574.68   207.9 2573.67   231.9 2572.98     249 2575.61   257.5 2574.89
   292.8 2574.92   305.6 2573.42   313.4 2572.12   322.6  2573.1   336.7 2575.53
   353.3 2574.89   380.7  2579.6   389.3 2582.02   402.7  2587.8   408.2 2589.34
   424.3 2597.07   430.2 2597.97   435.8 2600.54   441.8 2601.63   457.3 2601.58
#Mann= 3 ,-1,0
       0      .1       0   305.6    .045       0   322.6      .1       0
#XS Ineff= 2 , 0
          249.86 2579.23
Permanent Ineff=
       F       F
Bank Sta=305.6,322.6
XS Rating Curve= 0 ,0
Exp/Cntr(USF)=0,0
Exp/Cntr=0.3,0.1

Type RM Length L Ch R = 1 ,15573   ,74.5,71.1,66.6
XS GIS Cut Line= 4
2252883.60824801 657084.872454182252940.60368656657205.043559552
2253059.40140787657276.4595307452253204.98011838657347.188809908
#Sta/Elev= 30
       0  2620.8    35.8  2613.2    66.7  2605.5      76  2601.8    93.7  2601.2
     104 2597.68   122.7 2593.97   137.2 2589.06   155.8 2576.92   168.52572.263
   176.5    2570   179.2 2570.01   185.3 2571.93   199.8 2573.54   211.8 2572.39
   221.2  2572.4   235.2 2574.96     261 2573.89   326.6 2575.44   330.3 2576.32
   352.5 2586.21   365.9 2593.22   374.8 2595.04   383.1 2598.13   386.5 2598.71
   405.9 2598.73   410.4 2600.99   416.4 2605.26   423.7 2611.44   433.5 2616.29
#Mann= 3 ,-1,0
       0      .1       0   168.5    .045       0   185.3      .1       0
Bank Sta=168.5,185.3
XS Rating Curve= 0 ,0
Exp/Cntr(USF)=0,0
Exp/Cntr=0.3,0.1

Type RM Length L Ch R = 1 ,15502   ,156.4,159.2,162
XS GIS Cut Line= 4
2252741.39077176657254.3469569552252899.70552492657292.744735063
2253016.51183934 657298.924963342253195.73845935657385.448159208
#Sta/Elev= 30
       0 2669.27    32.5 2653.25    60.5 2642.51      76 2635.36    89.3 2630.64
   101.6 2624.73   118.1 2618.47   122.2 2616.16   127.2 2611.79   130.5 2610.62
   142.8 2609.18     151 2603.61   183.4 2587.95   201.8 2580.26   215.4 2573.12
   228.4 2570.05   239.5 2568.72   251.3 2570.65   267.5 2573.91   287.3  2572.5
   303.5 2575.77   337.2 2573.92   359.5 2574.95   380.2 2581.59   408.3  2594.5
   421.6  2597.4   439.4 2597.17   443.1 2598.29     464  2613.1   478.9 2620.66
#Mann= 3 ,-1,0
       0      .1       0   228.4    .045       0   251.3      .1       0
Bank Sta=228.4,251.3
XS Rating Curve= 0 ,0
Exp/Cntr(USF)=0,0
Exp/Cntr=0.3,0.1

Type RM Length L Ch R = 1 ,15343   ,140,138.3,136.7
XS GIS Cut Line= 2
 2252741.4338221 657369.120766562253200.07627717657532.739978812
#Sta/Elev= 30
       0 2643.27    15.7  2641.7    28.4 2637.88    64.8 2619.17    79.4 2617.06
    99.2 2607.57   113.3 2606.06   130.3 2598.02   138.8 2594.98   151.6 2588.44
   181.3 2570.11   185.5 2569.21   198.3 2569.15     2042567.697   215.3 2566.68
   221.62567.702     228 2569.32   236.5 2569.19   253.5 2572.41   318.3 2571.36
   346.5 2582.01   355.4 2586.42   372.4  2590.3   393.6 2590.51   416.8 2605.61
   443.6 2615.49   457.3 2621.49   470.1 2628.47   482.8 2630.27     487 2632.99
#Mann= 3 ,-1,0
       0      .1       0     204    .045       0   221.6      .1       0
Bank Sta=204,221.6
XS Rating Curve= 0 ,0
Exp/Cntr=0.3,0.1

Type RM Length L Ch R = 1 ,15205   ,217.6,222.3,222.7
XS GIS Cut Line= 3
   2252719.54406657458.0117035642252863.06269442657561.702200199
2253188.18615157 657605.84548522
#Sta/Elev= 30
       0 2609.65    45.2 2603.07    64.9 2598.37    73.7 2594.37    85.8 2592.16
   117.3 2572.22   125.9 2568.93   158.7 2568.55   173.5  2571.1   202.3 2567.27
   218.5 2568.58   226.6 2567.28     238 2568.58     263 2568.03   268.52566.829
   275.1 2565.02   283.1 2565.43   287.6 2566.82   307.4 2569.83   323.8 2569.43
   343.7 2575.14   355.8  2580.4     376 2585.86   400.2 2587.34   420.4 2599.58
   444.6 2608.25   468.8 2618.68     485 2621.81     493 2627.89   505.2 2633.03
#Mann= 3 ,-1,0
       0      .1       0   268.5    .045       0   287.6      .1       0
#XS Ineff= 2 , 0
                          308.65         2577.59
Permanent Ineff=
       F       F
Bank Sta=268.5,287.6
XS Rating Curve= 0 ,0
Exp/Cntr(USF)=0,0
Exp/Cntr=0.3,0.1