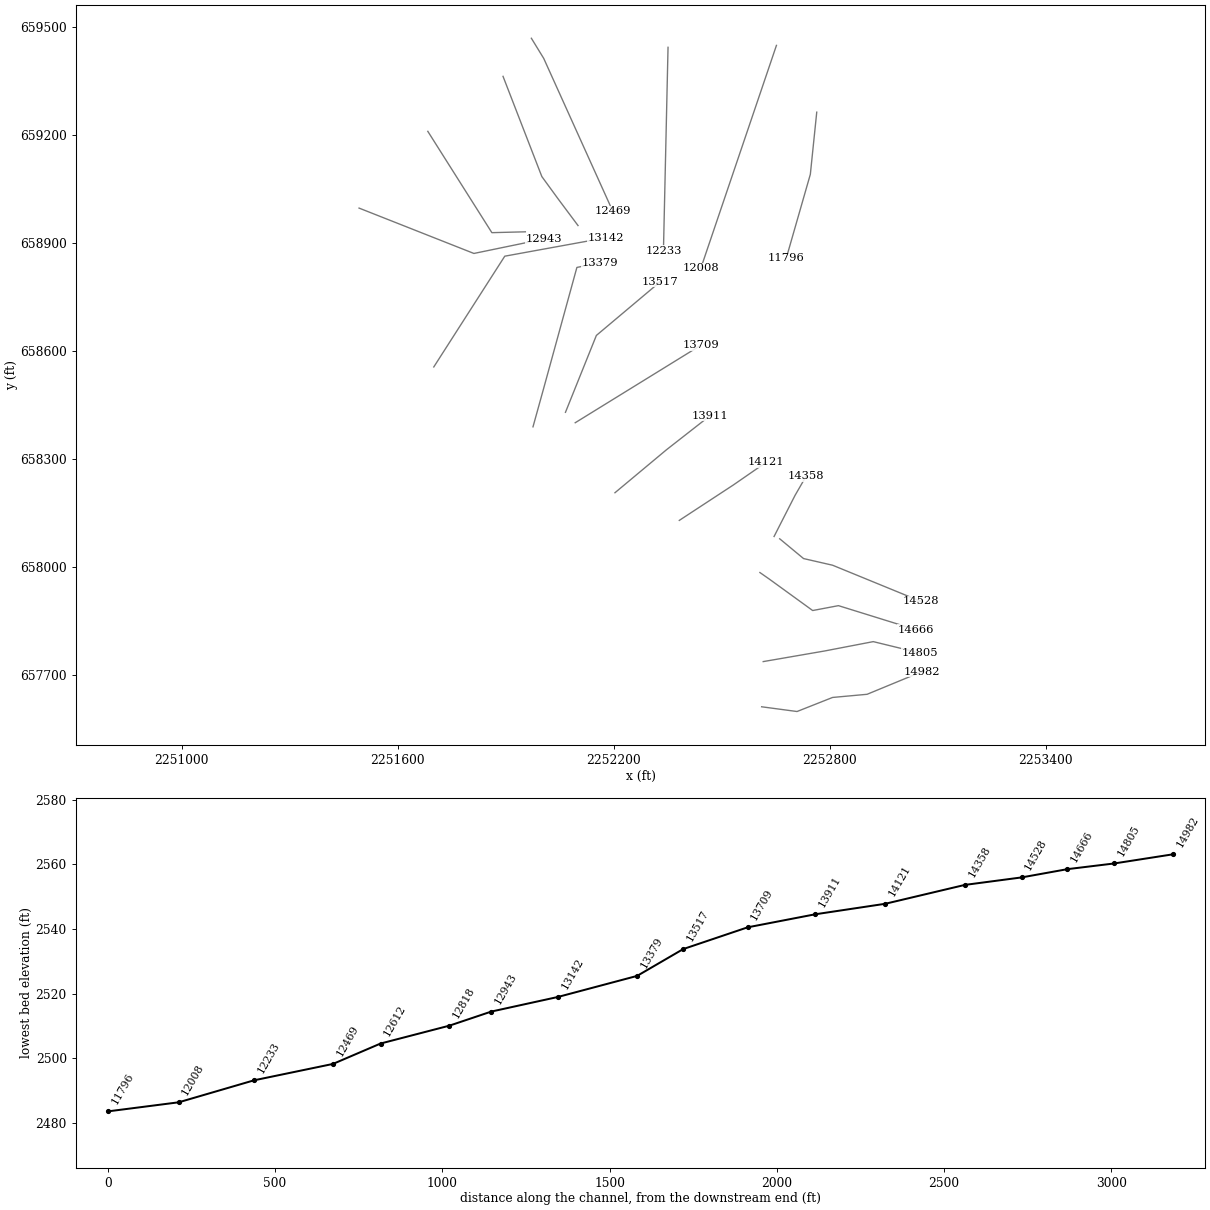
HEC-RAS study PANTHRN.prj: PANTHRN

--- PANTHRN.g01 (geometry) --- (continued)

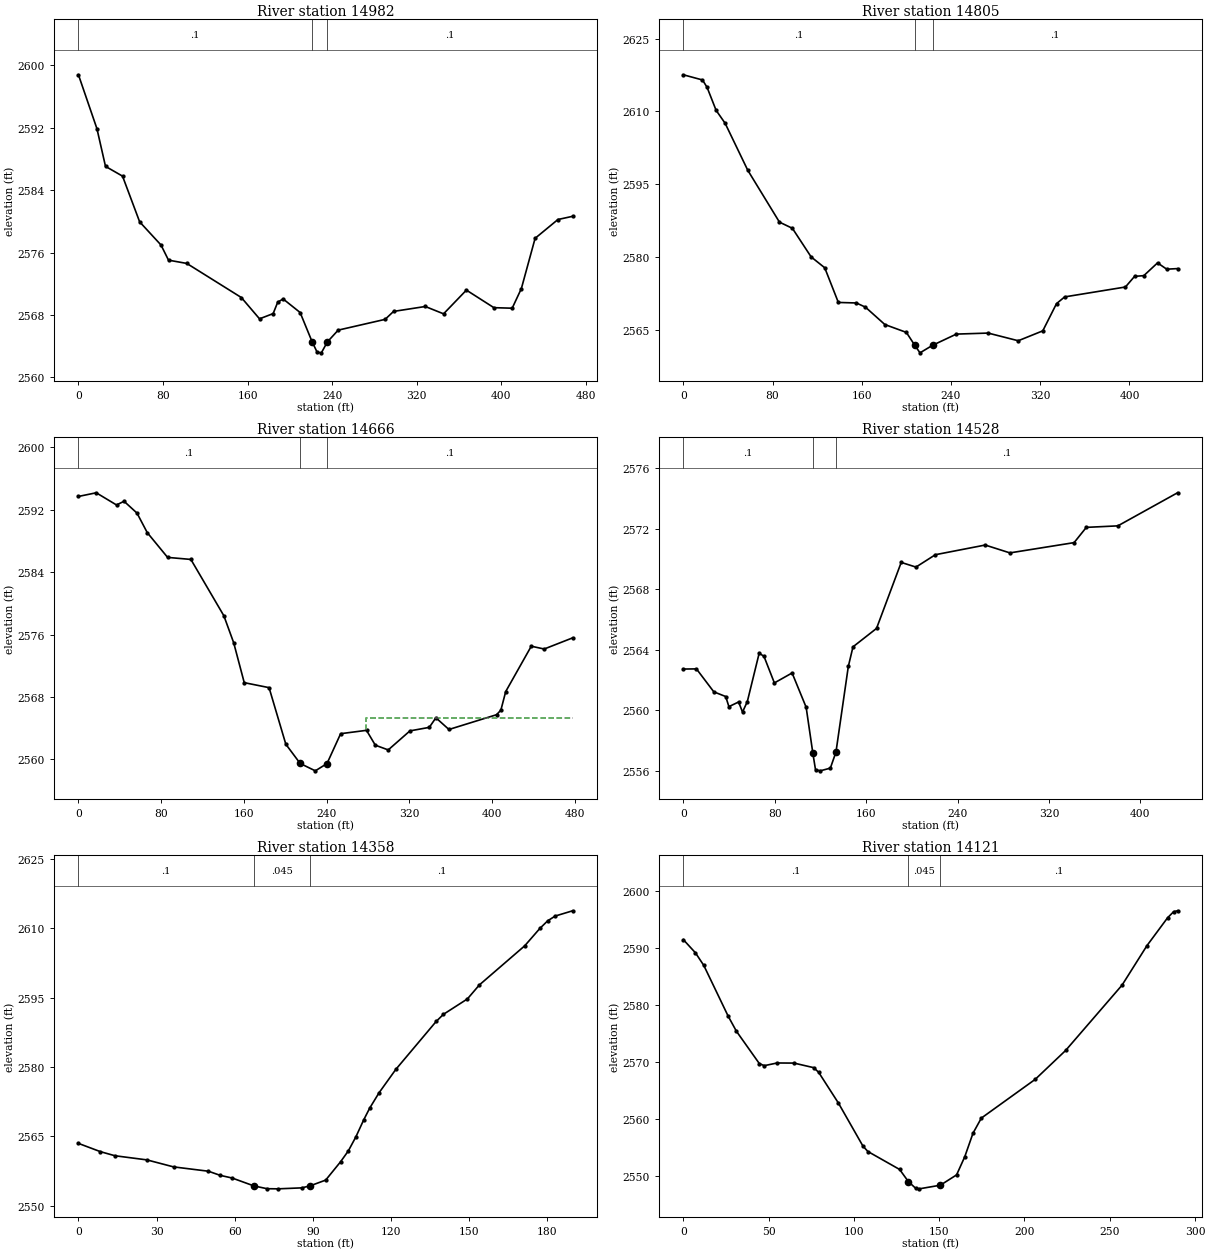
Type RM Length L Ch R = 1 ,14982   ,174.1,177.6,176.2
XS GIS Cut Line= 5
2252610.81068026657611.5930098522252709.14133578657598.442965281
2252807.80665079657637.490702211 2252903.7193245657646.276595985
2253057.03448993657709.597951223
#Sta/Elev= 30
       0 2598.79    17.5 2591.88    25.6 2587.05    41.7  2585.8    57.9 2579.94
    78.1 2576.97    85.2 2575.03   102.5 2574.61   154.1 2570.24   171.3 2567.51
   184.2 2568.18   188.5 2569.64   193.6 2570.06   209.7 2568.32     2212564.584
   225.8 2563.23   229.8 2563.15   235.52564.553   245.7 2566.06   290.1 2567.44
   298.1 2568.46   328.1 2569.09   345.4 2568.15     367 2571.19     393 2568.94
   410.3 2568.87     419 2571.39     432 2577.83   453.6 2580.24   467.5 2580.65
#Mann= 3 ,-1,0
       0      .1       0     221    .045       0   235.5      .1       0
Bank Sta=221,235.5
XS Rating Curve= 0 ,0
Exp/Cntr=0.3,0.1

Type RM Length L Ch R = 1 ,14805   ,139.8,139.2,133.3
XS GIS Cut Line= 4
2252615.23420287657737.1234682882252784.78779069657766.429026678
2252920.84931179657792.5947038112253049.58444328657761.195891251
#Sta/Elev= 30
       0 2617.56    17.2 2616.49    21.3 2614.98    29.4 2610.24    37.5 2607.57
    57.8 2597.89    86.2 2587.21    97.8 2585.94   114.6 2580.05   126.8 2577.81
     139 2570.67   155.2 2570.56   163.3  2569.7   180.7 2566.12     200  2564.5
   207.62561.822   212.2 2560.29   223.52561.847   244.8 2564.15   273.3 2564.36
   300.3 2562.78   322.3 2564.82   334.6 2570.42   341.9 2571.81   396.4 2573.85
   404.6 2576.04   412.9 2576.19   425.2 2578.82   433.4 2577.52   443.1 2577.64
#Mann= 3 ,-1,0
       0      .1       0   207.6    .045       0   223.5      .1       0
Bank Sta=207.6,223.5
XS Rating Curve= 0 ,0
Exp/Cntr(USF)=0,0
Exp/Cntr=0.3,0.1

Type RM Length L Ch R = 1 ,14666   ,139,137.3,134.1
XS GIS Cut Line= 5
2252606.04481706657984.525178721 2252633.0976549657965.612713238
 2252752.5930604657878.9781297622252824.15275443 657892.54217894
2253038.40646601657825.992574105
#Sta/Elev= 30
       0  2593.7    17.2 2594.17    36.8 2592.61    44.1 2593.08    56.6 2591.57
    66.5 2589.07    86.2 2585.89   108.7 2585.63   140.6 2578.41   150.1 2574.95
   160.3 2569.84   184.3  2569.2   200.5 2561.95  214.372559.486     229 2558.54
   240.3 2559.47   253.5  2563.3   278.5 2563.73     287 2561.83   299.5 2561.22
   320.5 2563.66   339.2 2564.11   345.6 2565.34   358.2 2563.84   404.2 2565.73
   408.4 2566.31   413.1  2568.7   437.8 2574.51   450.3 2574.15   477.8 2575.58
#Mann= 3 ,0,0
       0      .1       0  214.37    .045       0   240.3      .1       0
#XS Ineff= 2 , 0
                          278.45         2565.26
Permanent Ineff=
       F       F
Bank Sta=214.37,240.3
XS Rating Curve= 0 ,0
Exp/Cntr(USF)=0,0
Exp/Cntr=0.3,0.1

Type RM Length L Ch R = 1 ,14528   ,158.9,169.8,185.6
XS GIS Cut Line= 4
2252661.03105066658078.247373574 2252727.2692912658023.337870467
2252807.81358657 658004.871609262253051.97075304657904.834992443
#Sta/Elev= 30
       0 2562.72    11.5 2562.73    26.7 2561.21    37.1  2560.9    39.9 2560.23
    48.4 2560.54    51.8 2559.87      56 2560.56    66.4 2563.77    70.6 2563.56
    79.7  2561.8    95.2 2562.46   107.5 2560.19   113.42557.132   115.7 2556.05
   119.8 2555.98   128.7 2556.16   133.62557.226   144.4 2562.89   148.5 2564.19
   169.1 2565.41   190.7 2569.78   203.6 2569.47   220.6 2570.29   264.2 2570.93
   285.8 2570.41     342 2571.09   352.7  2572.1   380.3  2572.2   432.5 2574.39
#Mann= 3 ,-1,0
       0      .1       0   113.4    .045       0   133.6      .1       0
Bank Sta=113.4,133.6
XS Rating Curve= 0 ,0
Exp/Cntr(USF)=0,0
Exp/Cntr=0.3,0.1

Type RM Length L Ch R = 1 ,14358   ,240.2,237.8,231.2
XS GIS Cut Line= 4
2252645.37344232658084.6772830732252664.04696341658121.372878991
2252703.89205655658199.367529391 2252734.3687295658252.099667079
#Sta/Elev= 30
       0 2563.49     8.4 2561.71      14 2560.82    26.3 2559.92    36.5 2558.41
    49.9 2557.47    54.4 2556.58      59    2556   67.352554.294    72.4 2553.69
    76.6 2553.66    85.7 2553.87    88.92554.302    94.9 2555.55   100.6  2559.5
   103.6 2561.87   106.5 2564.91   109.5 2568.58   111.8 2571.12   115.4 2574.45
   121.8 2579.48   137.3 2589.86   140.1 2591.41   149.3 2594.74   153.9 2597.77
   171.3 2606.23   177.1 2609.98   180.1 2611.63     183 2612.67   189.7 2613.81
#Mann= 3 ,0,0
       0      .1       0   67.35    .045       0    88.9      .1       0
Bank Sta=67.35,88.9
XS Rating Curve= 0 ,0
Exp/Cntr(USF)=0,0
Exp/Cntr=0.3,0.1

Type RM Length L Ch R = 1 ,14121   ,207.1,209.4,208.5
XS GIS Cut Line= 3
2252382.15011983658129.3961339342252532.20504506658227.737214875
2252622.91621455658290.472042371
#Sta/Elev= 30
       0 2591.55     7.1 2589.24      12 2587.03    26.3 2578.12    31.1 2575.49
    44.6 2569.79    47.5 2569.44      55 2569.91    64.9 2569.89    76.4 2569.09
    79.3 2568.29    90.9 2562.89   105.3 2555.33   108.2 2554.38   126.8 2551.23
   131.92549.117   136.3  2547.9   138.3 2547.83   150.7 2548.47   160.2 2550.28
     165 2553.47   169.8 2557.58   174.7 2560.24   206.3 2567.04   224.1  2572.1
   257.2 2583.57   271.8  2590.5   283.9 2595.39   287.4 2596.44   289.7 2596.61
#Mann= 3 ,-1,0
       0      .1       0   131.9    .045       0   150.7      .1       0
Bank Sta=131.9,150.7
XS Rating Curve= 0 ,0
Exp/Cntr(USF)=0,0
Exp/Cntr=0.3,0.1

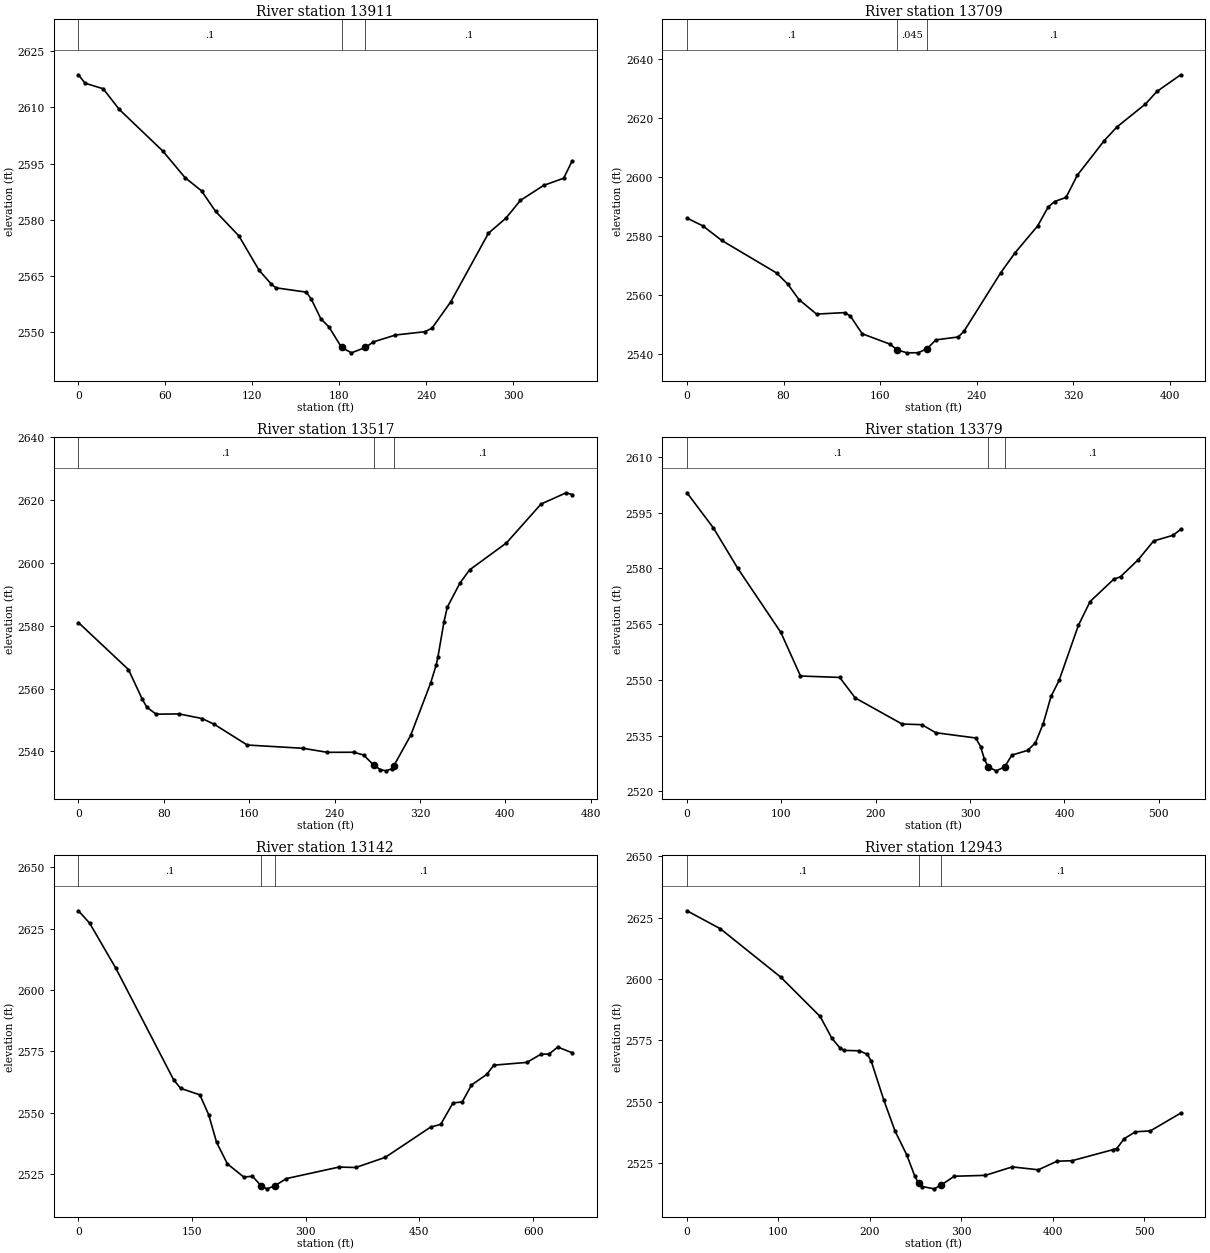
Type RM Length L Ch R = 1 ,13911   ,201.9,202,200.2
XS GIS Cut Line= 3
 2252203.4404253 658206.21728771     2252346.502      658325.605
 2252468.2370779658420.775840209
#Sta/Elev= 30
       0 2618.67     4.6 2616.42    17.1 2614.95    28.2 2609.44    58.3 2598.33
    73.6 2591.27      85 2587.74    94.7 2582.27   110.8 2575.73   124.7 2566.59
   133.3 2562.83   136.4  2561.9   157.3 2560.76   160.7 2558.95   167.3  2553.7
     173 2551.46   181.72546.014   188.5 2544.58   198.12546.009   203.7  2547.5
   218.9 2549.33   239.2 2550.21   244.1 2551.15   257.1  2558.2   283.1 2576.46
   295.1 2580.45   305.2 2585.21   321.2  2589.2     335  2591.1   340.9 2595.73
#Mann= 3 ,-1,0
       0      .1       0   181.7    .045       0   198.1      .1       0
Bank Sta=181.7,198.1
XS Rating Curve= 0 ,0
Exp/Cntr=0.3,0.1

Type RM Length L Ch R = 1 ,13709   ,191,192.6,191.8
XS GIS Cut Line= 2
2252093.06125258 658400.681874462252441.07627861658615.407003515
#Sta/Elev= 30
       0  2586.2    13.1 2583.57    28.8 2578.62    74.2 2567.61    83.6 2563.78
    92.7 2558.61   107.3 2553.67   130.6 2554.18   135.3 2553.02   145.1 2547.01
   168.2 2543.49   174.1 2541.54   182.3 2540.55   191.6 2540.59     199 2542.01
   206.1 2544.94   224.6 2545.92   229.3  2547.8   259.9 2567.71   271.6 2574.39
   290.4 2583.53   299.1 2589.93   304.5 2591.81   313.9 2593.19   323.3 2600.73
   345.6 2612.45   356.2 2617.12   379.7 2624.84   389.2 2629.09   408.9 2634.74
#Mann= 3 ,-1,0
       0      .1       0   174.1    .045       0     199      .1       0
Bank Sta=174.1,199
XS Rating Curve= 0 ,0
Exp/Cntr(USF)=0,0
Exp/Cntr=0.3,0.1

Type RM Length L Ch R = 1 ,13517   ,132.1,137.9,143.5
XS GIS Cut Line= 3
2252065.95295035658429.6583894632252151.77637135658643.170314876
2252329.70297586658792.837988082
#Sta/Elev= 30
       0 2581.04    46.9 2566.07    59.8 2556.65    64.1 2554.08    72.8 2551.87
    94.3 2551.95   115.9 2550.48   127.4 2548.62   158.2 2542.05   210.4 2541.01
   233.2 2539.72   258.1 2539.75   267.2 2538.86   276.7 2535.64   282.9 2534.22
   288.1 2533.83   293.4 2534.47   295.4 2535.39   311.3 2545.12   329.9 2561.72
   335.2 2567.51   336.9 2570.22   342.5  2581.3   345.6 2585.94   357.5 2593.65
   366.5 2597.81     401 2606.38   433.4 2618.76   456.9 2622.35   462.6 2621.76
#Mann= 3 ,-1,0
       0      .1       0   276.7    .045       0   295.4      .1       0
Bank Sta=276.7,295.4
XS Rating Curve= 0 ,0
Exp/Cntr(USF)=0,0
Exp/Cntr=0.3,0.1

Type RM Length L Ch R = 1 ,13379   ,239.2,236.7,233.9
XS GIS Cut Line= 4
2251975.76974103 658389.274136922252005.07529942 658494.98347254
2252097.69684438658832.1476236732252160.33790507658844.621525654
#Sta/Elev= 30
       0 2600.36      28 2590.91    53.9    2580    99.5 2562.78   120.3 2551.05
   161.8 2550.67   178.3 2545.15   227.9 2538.13   248.9 2537.95   263.7 2535.79
     306 2534.37   311.1 2532.08   315.2 2528.65   319.12526.605   327.7 2525.53
   336.6 2526.59   344.3 2529.76   360.9 2531.03   369.2 2533.04   377.5 2538.23
   385.8 2545.57   394.4 2549.92   414.8  2564.7   427.2  2571.1   452.1 2577.07
   459.4 2577.77   478.2 2582.35   494.5  2587.4   514.9  2588.9   523.2  2590.5
#Mann= 3 ,-1,0
       0      .1       0   319.1    .045       0   336.6      .1       0
Bank Sta=319.1,336.6
XS Rating Curve= 0 ,0
Exp/Cntr(USF)=0,0
Exp/Cntr=0.3,0.1

Type RM Length L Ch R = 1 ,13142   ,216.2,199.3,184.5
XS GIS Cut Line= 3
2251700.22039156658555.672384703 2251897.3905101658863.365537724
2252178.93319605658914.650264906
#Sta/Elev= 30
       0 2632.33    14.7 2627.33    49.3 2608.95   125.6  2563.5   134.8 2559.98
   160.3 2557.31   171.9  2549.2   182.3    2538   196.6  2529.2   218.2 2523.83
   229.7 2524.15   241.22520.212   248.8 2519.02   258.92520.204   274.2 2523.18
   343.8 2527.89     366 2527.72   404.9 2531.84   464.8 2544.18   478.1  2545.3
   494.3 2554.04   506.5 2554.42   518.7 2561.32     539 2565.69   548.2 2569.42
   591.9 2570.55   610.2 2573.86   621.1 2573.96   632.6  2576.8   651.6 2574.47
#Mann= 3 ,-1,0
       0      .1       0   241.2    .045       0   258.9      .1       0
Bank Sta=241.2,258.9
XS Rating Curve= 0 ,0
Exp/Cntr=0.3,0.1

Type RM Length L Ch R = 1 ,12943   ,132.6,125.1,117.8
XS GIS Cut Line= 3
2251492.62508131658996.9747561522251811.67006999658870.951985625
2252004.69228814658910.832609209
#Sta/Elev= 30
       0 2627.78    36.5 2620.47   102.7 2600.71   145.7 2584.71   158.6  2575.8
   167.2 2571.98   171.5 2570.91   188.7 2570.73   197.4 2569.26   201.7 2566.38
   215.3 2550.69   227.6 2538.06   240.4 2528.35     249 2519.89   253.3 2516.72
   257.6 2515.42   270.5  2514.5   278.42516.132   292.4 2519.63   326.4    2520
   355.8 2523.44   384.4 2522.26   404.8 2525.76   421.2 2525.96   466.1 2530.47
   470.2 2530.93   478.3 2534.94   490.6 2537.74   506.9 2538.11   540.1 2545.35
#Mann= 3 ,-1,0
       0      .1       0   253.3    .045       0   278.4      .1       0
Bank Sta=253.3,278.4
XS Rating Curve= 0 ,0
Exp/Cntr(USF)=0,0
Exp/Cntr=0.3,0.1

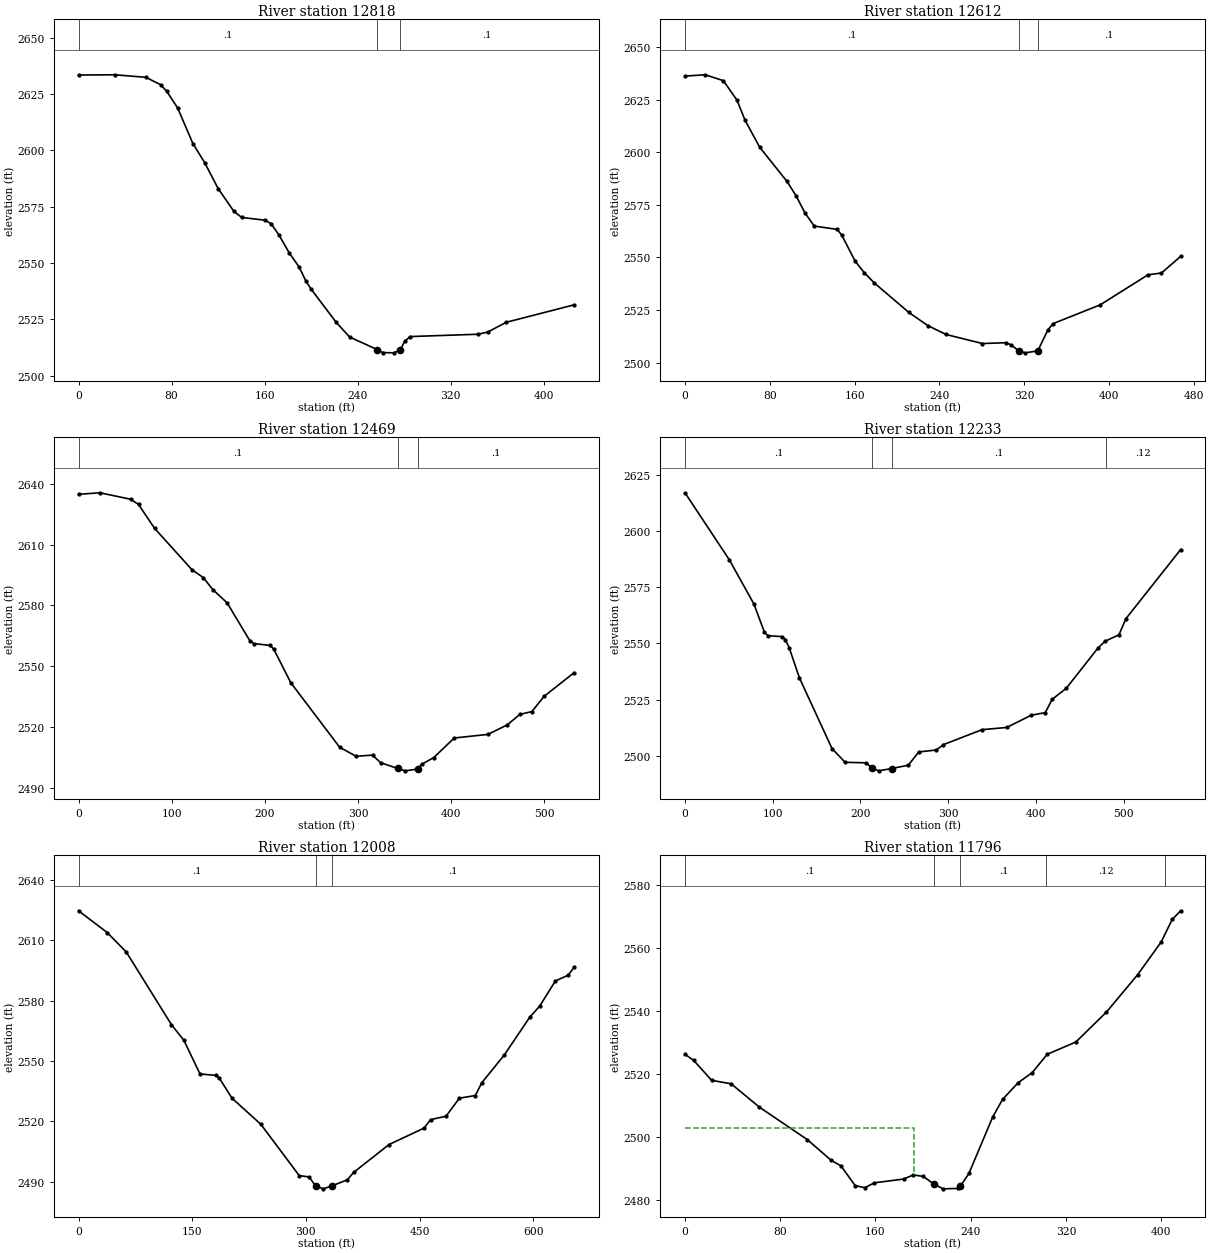
Type RM Length L Ch R = 1 ,12818   ,205.4,205.9,206.1
XS GIS Cut Line= 3
2251683.63194278659210.1448503642251861.55854729658928.718456305
2251954.57826731658931.075039016
#Sta/Elev= 30
       0 2633.38      31 2633.49    57.9 2632.37    70.7 2629.03    75.9 2626.08
    85.2 2618.78    98.3 2602.99   108.4 2594.55     120 2583.03   133.6 2572.85
   140.3  2570.2   160.6 2568.97   165.7 2567.29   172.2 2562.49     181  2554.6
   189.6 2548.22   195.3 2542.12   199.9 2538.43   221.4 2523.72     233 2517.16
   256.7  2511.6   261.4 2510.27   270.9 2510.15   276.5 2511.41   280.4 2515.34
   285.1 2517.37   343.4  2518.4   351.6 2519.34   367.6  2523.7     426 2531.45
#Mann= 3 ,-1,0
       0      .1       0   256.7    .045       0   276.5      .1       0
Bank Sta=256.7,276.5
XS Rating Curve= 0 ,0
Exp/Cntr(USF)=0,0
Exp/Cntr=0.3,0.1

Type RM Length L Ch R = 1 ,12612   ,143.4,142.4,138.5
XS GIS Cut Line= 4
2251892.54300019 659362.944385612252000.34558998659084.541580903
2252045.35055465659022.7905828672252100.82179018658948.480059806
#Sta/Elev= 30
       0 2636.19    19.1 2636.81    36.2 2634.02    49.1 2624.73    56.7 2615.18
    70.5 2602.38    96.3 2586.08   104.8  2579.3   113.4 2570.98     122 2564.89
   143.4 2563.32   147.7 2560.77   160.6  2548.2   169.2 2542.71   178.7 2537.83
   211.3  2523.8   229.2 2517.56   246.4 2513.34   280.7 2509.04   302.7 2509.43
   307.7 2508.45   315.1 2505.45   320.9 2504.62   332.9 2505.54   342.3 2515.39
   347.3  2518.5   391.9 2527.46   436.9 2541.72   449.6 2542.57   467.7 2550.46
#Mann= 3 ,-1,0
       0      .1       0   315.1    .045       0   332.9      .1       0
Bank Sta=315.1,332.9
XS Rating Curve= 0 ,0
Exp/Cntr(USF)=0,0
Exp/Cntr=0.3,0.1

Type RM Length L Ch R = 1 ,12469   ,238.7,236.2,229
XS GIS Cut Line= 3
2251971.24337189659468.8062739242252005.59778832659412.749584746
2252197.49912169658987.928855998
#Sta/Elev= 30
       0 2634.79      23 2635.54    55.9 2632.35    64.4 2629.77    81.7 2617.95
   121.8 2597.53   133.9 2593.68   144.3 2587.68   159.5 2581.21   183.8 2562.57
   188.3 2561.14   205.7 2560.17   209.5 2558.38   227.8 2541.81   280.3 2509.92
   297.9 2505.51   315.5 2506.06   324.2 2502.34   342.42499.506   350.6 2498.31
   363.8 2499.18   368.1  2501.5   381.3 2504.88   403.2 2514.52   439.3 2516.29
   460.3 2521.03   473.5 2526.14   486.6 2527.59   499.5 2535.02   531.9 2546.78
#Mann= 3 ,-1,0
       0      .1       0   342.4    .045       0   363.8      .1       0
Bank Sta=342.4,363.8
XS Rating Curve= 0 ,0
Exp/Cntr=0.3,0.1

Type RM Length L Ch R = 1 ,12233   ,225.7,224.9,219.2
XS GIS Cut Line= 2
2252350.85610085659443.6377403012252338.09430131658878.928110341
#Sta/Elev= 30
       0 2617.08    50.5 2587.26    78.5  2567.6    90.5 2555.05    94.5 2553.43
   110.5 2553.03   114.5 2551.63   118.7 2548.14   130.5 2534.58   167.6 2503.15
   182.5 2497.04   206.5 2496.81   213.62494.374   220.8 2493.24   235.52494.259
   254.5 2495.75   266.5 2501.65   286.5 2502.53   294.5  2504.9   338.5 2511.58
   366.6 2512.55   394.6 2518.01   410.6 2519.16   418.6 2525.13   434.6 2530.02
   470.6 2547.89   478.6 2550.92   494.6 2553.84   502.6 2561.02   564.9 2591.79
#Mann= 4 ,-1,0
       0      .1       0   213.6    .045       0   235.5      .1       0
     480     .12       0
Bank Sta=213.6,235.5
XS Rating Curve= 0 ,0
Exp/Cntr(USF)=0,0
Exp/Cntr=0.3,0.1

Type RM Length L Ch R = 1 ,12008   ,210.8,211.8,211.9
XS GIS Cut Line= 2
2252651.94470295659448.9478025212252441.87392851658829.676665384
#Sta/Elev= 30
       0 2624.78    37.8 2613.97    63.1 2604.22   122.6 2568.12   139.1 2560.28
   160.3 2543.58   181.4  2542.9   185.6 2541.62   202.5 2531.54   240.5 2518.58
   291.2 2493.04   303.9 2492.41   312.72488.009     323 2486.45   334.92488.012
   354.6 2490.93     363 2494.64   409.7  2508.5   455.9 2516.67   464.4 2520.87
   484.9 2522.59   502.4 2531.54   523.5 2532.87     532 2539.22   561.5 2552.93
   595.3 2571.82   608.4 2577.34   629.1 2589.86     646 2592.74   653.9 2596.74
#Mann= 3 ,-1,0
       0      .1       0   312.7    .045       0   334.9      .1       0
Bank Sta=312.7,334.9
XS Rating Curve= 0 ,0
Exp/Cntr=0.3,0.1

Type RM Length L Ch R = 1 ,11796   ,98,101.8,104.4
XS GIS Cut Line= 3
2252763.89491767659263.4752210252252746.10225722659090.781751941
2252679.11812376658857.383911906
#Sta/Elev= 30
       0 2526.28     7.4 2524.33    22.4 2518.03    38.8 2516.93    62.6 2509.51
   102.8 2499.23   122.9 2492.66     131 2490.93     143 2484.66   151.1 2484.01
   159.1 2485.55   183.6 2486.73   191.9 2488.06   200.2 2487.56   209.12485.174
   216.9 2483.64   229.4 2483.77   231.4 2484.48   238.6 2488.56   258.5  2506.4
   266.8 2511.99   279.9 2517.29   291.8  2520.5   304.3 2526.29   328.4 2530.18
   354.1 2539.69   380.2 2551.47     400 2561.86   409.3 2569.02   416.4 2571.78
#Mann= 5 ,-1,0
       0      .1       0   209.1    .045       0   231.4      .1       0
  303.61     .12       0  403.61      .1       0
#XS Ineff= 2 , 0
          192.76 2502.86
Permanent Ineff=
       F       F
Bank Sta=209.1,231.4
XS Rating Curve= 0 ,0
Exp/Cntr(USF)=0,0
Exp/Cntr=0.3,0.1