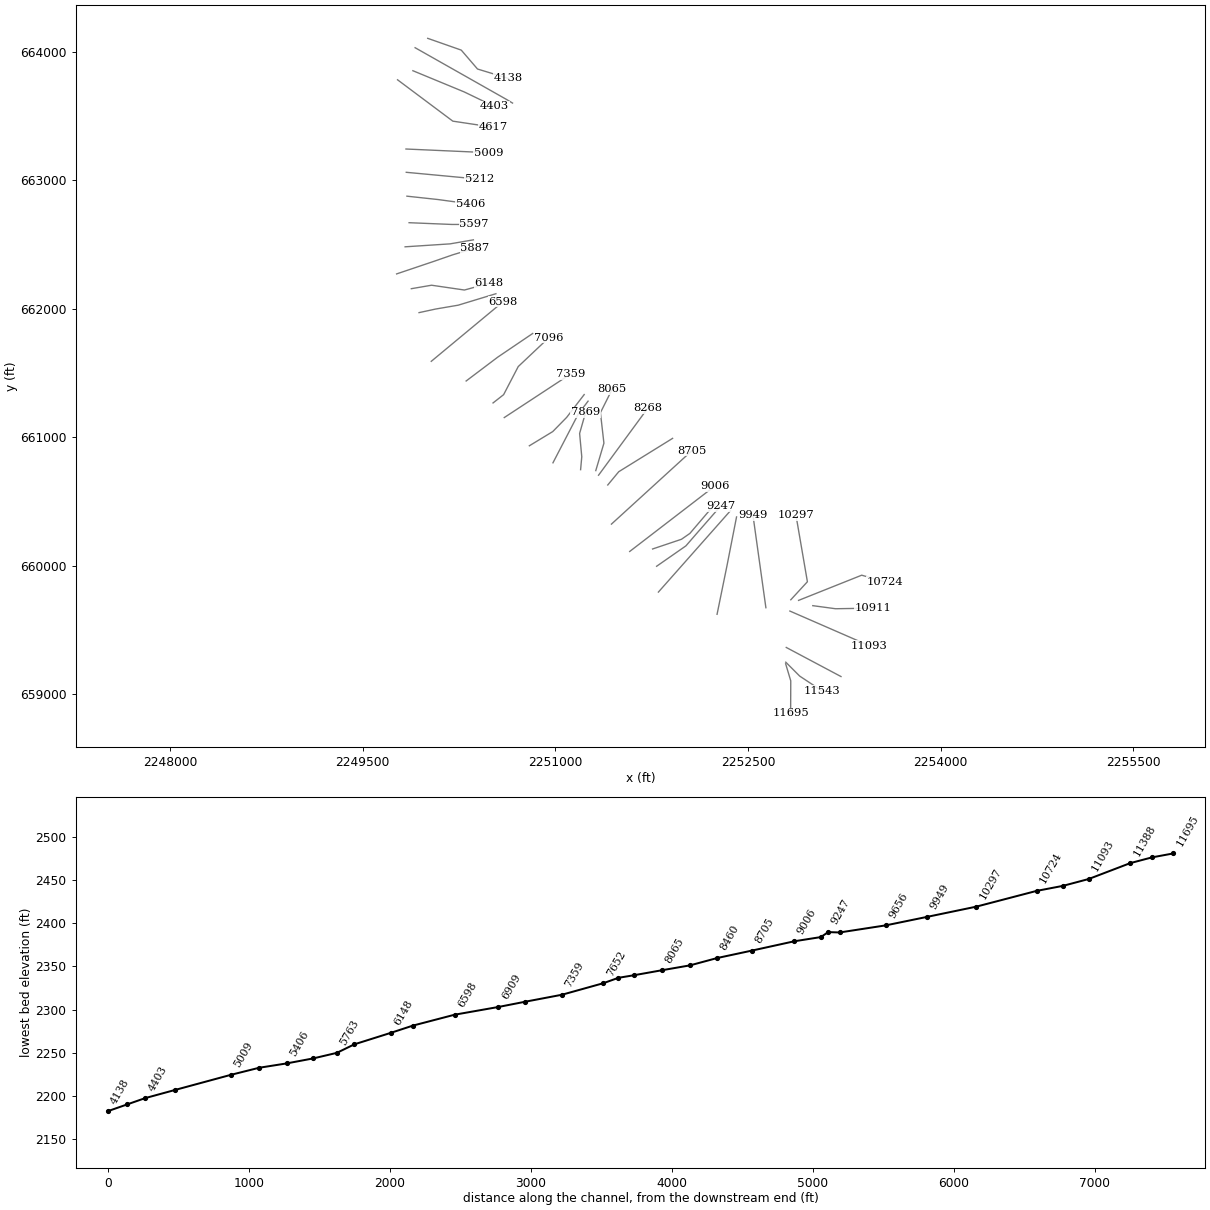
HEC-RAS study PANTHRN.prj: PANTHRN

--- PANTHRN.g01 (geometry) --- (continued)

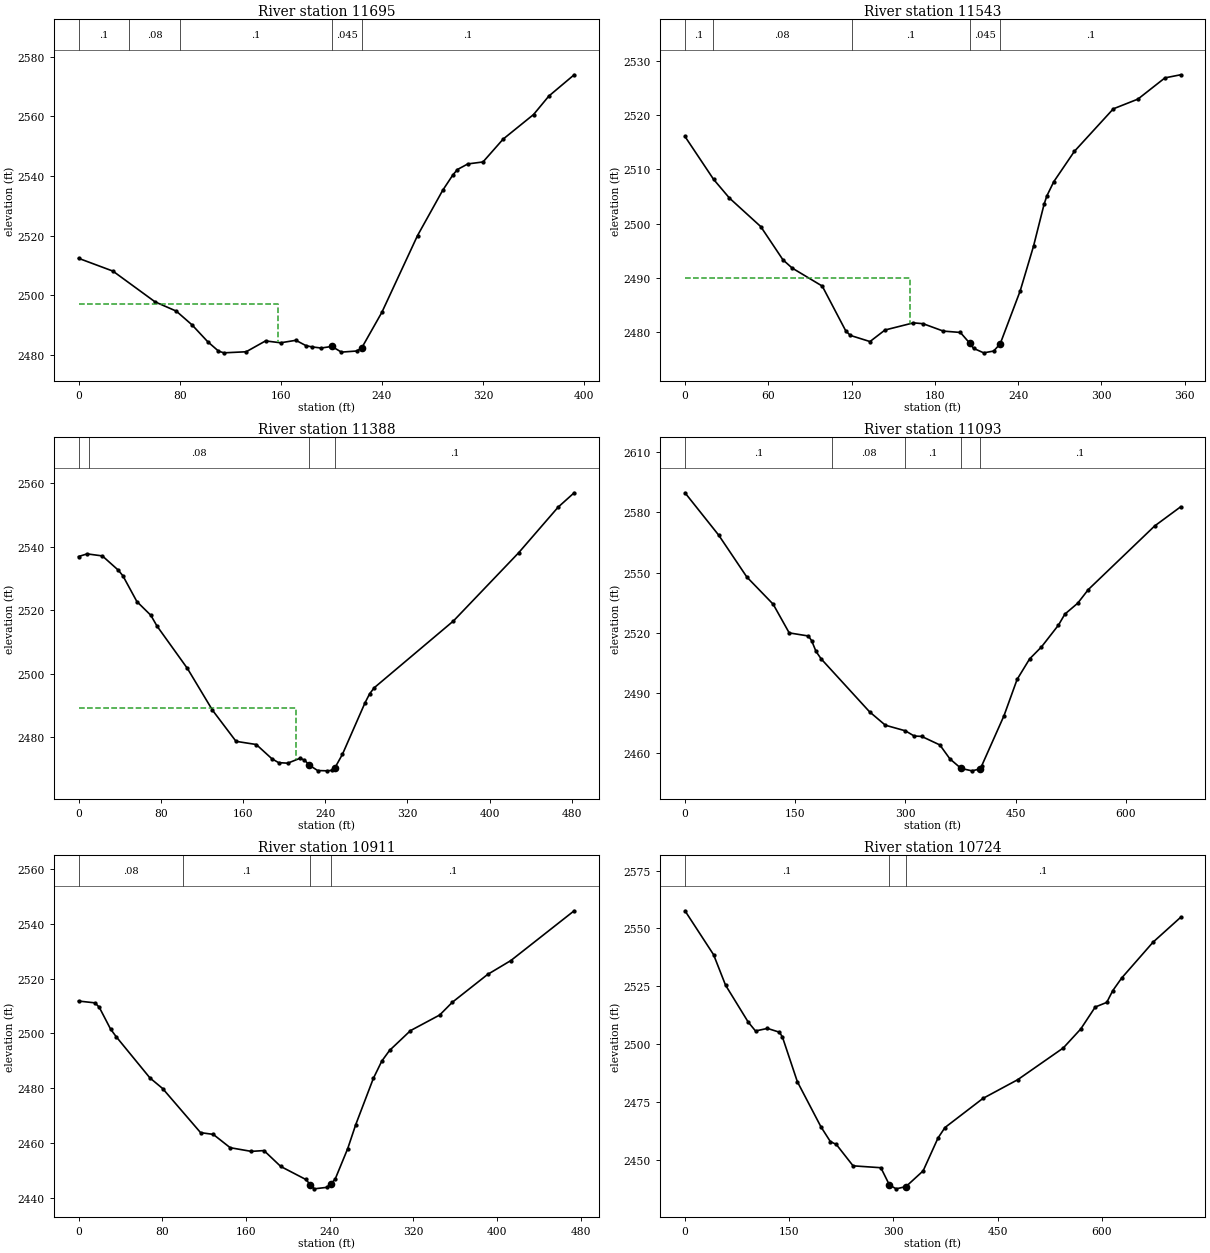
Type RM Length L Ch R = 1 ,11695   ,140.1,151.8,162.7
XS GIS Cut Line= 3
2252793.20047606 659235.216289722252832.97230531 659102.29464988
2252831.92567822658849.010895223
#Sta/Elev= 30
       0 2512.42    27.2 2508.13    60.6 2497.81    77.3 2494.73    89.8 2490.11
   102.3 2484.43   110.7 2481.34   114.9 2480.75   132.6 2481.11   147.9 2484.74
   159.9 2484.12   171.9 2484.95   179.9 2483.16   184.5 2482.75   191.9 2482.36
   200.4  2482.9   207.9 2480.99   219.9 2481.36   223.9 2482.34   239.9 2494.31
   268.1 2520.02     288 2535.17     296  2540.3   299.7 2542.16   307.9 2544.03
   319.9 2544.69   335.8 2552.33   359.9 2560.58     372 2566.77     392 2573.89
#Mann= 5 ,-1,0
       0      .1       0      40     .08       0      80      .1       0
   200.4    .045       0   223.9      .1       0
#XS Ineff= 2 , 0
          158.06 2496.96
Permanent Ineff=
       T       F
Bank Sta=200.4,223.9
XS Rating Curve= 0 ,0
Exp/Cntr(USF)=0,0
Exp/Cntr=0.3,0.1

Type RM Length L Ch R = 1 ,11543   ,155.7,155.1,157.4
XS GIS Cut Line= 3
2252794.24710315659247.7758147452252903.09632002659138.926597868
2253072.64990785659026.937499734
#Sta/Elev= 30
       0 2516.07    20.6 2508.17      32 2504.72    54.6 2499.45    70.6 2493.32
    77.2 2491.81    98.9 2488.48   115.9 2480.19   119.2 2479.38   133.3 2478.25
   144.1 2480.38   164.6  2481.7   171.6 2481.54   186.1 2480.18   198.4 2479.93
   205.1 2477.96   207.9    2477   215.2 2476.17   222.4  2476.5   227.1 2477.83
   241.5 2487.59   251.1 2495.83   258.7 2503.55   260.7  2505.1   265.7 2507.73
   280.5 2513.31   308.6 2521.17   326.3 2522.96   345.8 2526.88   357.1 2527.45
#Mann= 5 ,-1,0
       0      .1       0      20     .08       0     120      .1       0
   205.1    .045       0   227.1      .1       0
#XS Ineff= 2 , 0
           161.9 2489.97
Permanent Ineff=
       F       F
Bank Sta=205.1,227.1
XS Rating Curve= 0 ,0
Exp/Cntr(USF)=0,0
Exp/Cntr=0.3,0.1

Type RM Length L Ch R = 1 ,11388   ,295.8,294.1,297.7
XS GIS Cut Line= 2
2252798.03798538659362.4270905382253223.96304526 659135.90514858
#Sta/Elev= 30
       0 2536.95     8.4 2537.78    23.2 2537.14    38.7 2532.66    43.2 2530.88
    56.8 2522.77    70.4 2518.44    76.4 2515.05     106  2501.7   130.4 2488.56
   153.3 2478.76     173 2477.76   188.2 2473.28   194.7 2472.06   203.6 2471.88
   215.4  2473.4   219.9 2472.88   224.7 2471.24   232.7 2469.57   242.1 2469.47
   247.1 2469.64   249.7 2470.51   256.9  2474.7   278.8 2490.86   283.3 2493.71
   287.8 2495.63   364.9 2516.66   428.3 2538.11   466.8  2552.5   482.4 2557.02
#Mann= 4 ,-1,0
       0      .1       0      10     .08       0   224.7    .045       0
   249.7      .1       0
#XS Ineff= 2 , 0
           211.7  2489.4
Permanent Ineff=
       F       F
Bank Sta=224.7,249.7
XS Rating Curve= 0 ,0
Exp/Cntr(USF)=0,0
Exp/Cntr=0.3,0.1

Type RM Length L Ch R = 1 ,11093   ,179.7,182.7,188.6
XS GIS Cut Line= 2
2252826.10681687659645.9876919172253444.62608395659376.178041002
#Sta/Elev= 30
       0 2589.75    45.9 2568.63    84.2 2547.76   120.1 2534.17   141.9 2519.89
   168.1 2518.34   172.5 2515.95   178.4 2510.65   185.5 2506.89   251.3 2480.54
   272.8 2473.86     300 2471.07   312.1 2468.47   322.2 2468.28     347 2464.02
   360.7 2457.06   375.9 2452.31   390.7 2451.11     4012452.006   403.7 2453.39
   434.3 2478.58   452.2 2496.72   469.2 2506.92   485.3 2512.88   508.5 2523.79
   517.2 2529.25   534.7  2534.7   549.1 2541.49   639.4 2573.19   674.8 2582.75
#Mann= 5 ,-1,0
       0      .1       0     200     .08       0     300      .1       0
   375.9    .045       0     401      .1       0
Bank Sta=375.9,401
XS Rating Curve= 0 ,0
Exp/Cntr=0.3,0.1

Type RM Length L Ch R = 1 ,10911   ,184.1,186.9,191.4
XS GIS Cut Line= 3
2253004.51497977659687.9688669442253181.58494849659664.040492793
2253476.70156302659668.826167623
#Sta/Elev= 30
       0  2511.8    15.8 2511.13    19.8 2509.54    30.6 2501.59      36 2498.78
    68.3 2483.69    80.4 2479.84   116.7 2463.71   128.8 2463.08     145 2458.21
   165.1 2456.87   177.3 2457.16   193.3 2451.36   217.3  2446.6   221.7 2444.65
   225.3 2443.18   237.3 2443.72   241.4  2445.1   245.3  2446.7   257.3 2457.85
     265 2466.64   281.8  2483.5   289.9 2489.85   297.3 2493.74   317.3 2500.98
   345.3 2506.71   357.3 2511.34     391  2521.5   413.3  2526.6   473.8 2544.78
#Mann= 4 ,-1,0
       0     .08       0     100      .1       0   221.7    .045       0
   241.4      .1       0
Bank Sta=221.7,241.4
XS Rating Curve= 0 ,0
Exp/Cntr(USF)=0,0
Exp/Cntr=0.3,0.1

Type RM Length L Ch R = 1 ,10724   ,407.1,427.2,440.1
XS GIS Cut Line= 3
2252893.91411394659729.1327236342253385.24339649659925.345391669
2253562.31336521659874.298193481
#Sta/Elev= 30
       0 2557.59    41.2 2538.58    58.4 2525.41      91 2509.46   101.5 2505.61
   118.7 2506.72     136 2505.07   140.3 2502.95   161.7 2483.69   195.7 2464.14
   209.2 2457.79   217.8 2456.54   241.9 2447.29   281.9 2446.47   294.2 2439.03
   303.9 2437.34     3182438.309   342.7  2445.1   364.2 2459.36   374.2 2463.86
   428.8 2476.44   478.9 2484.55   544.5 2498.29   569.6 2506.49   590.4 2515.97
     607 2517.97   615.6 2523.04   628.5 2528.53   673.6 2544.01   713.3 2554.76
#Mann= 3 ,-1,0
       0      .1       0   294.2    .045       0     318      .1       0
Bank Sta=294.2,318
XS Rating Curve= 0 ,0
Exp/Cntr(USF)=0,0
Exp/Cntr=0.3,0.1

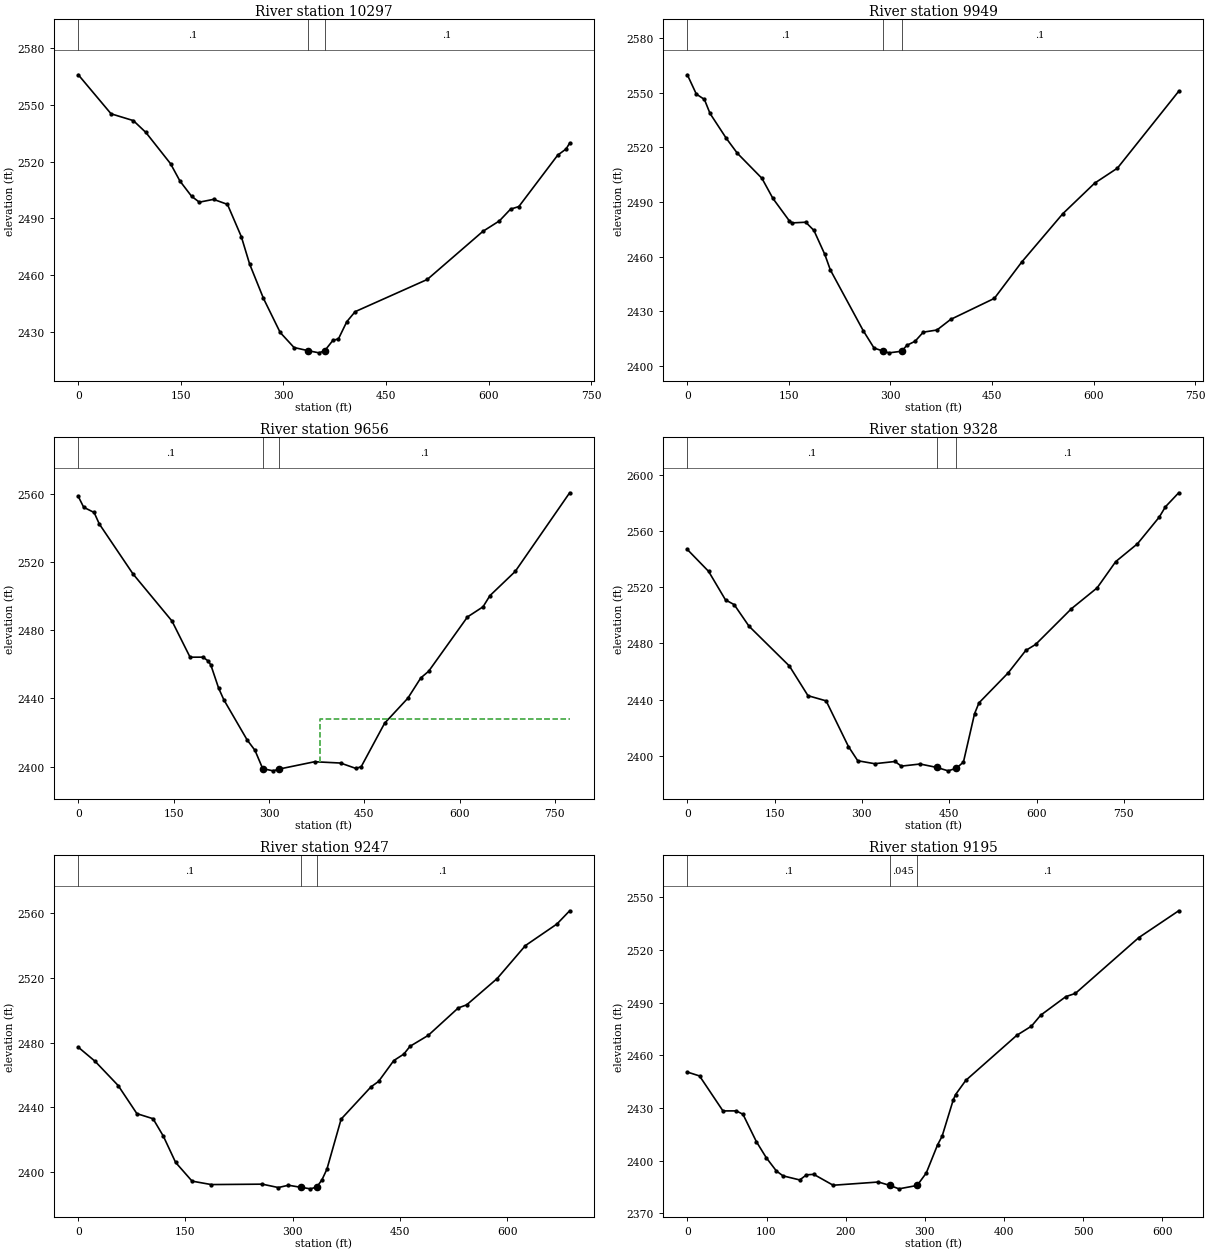
Type RM Length L Ch R = 1 ,10297   ,347.5,347.8,347.2
XS GIS Cut Line= 3
2252833.29556609659733.918398465 2252962.5087865659874.298193481
2252873.17618967660394.341525018
#Sta/Elev= 30
       0 2565.77    47.9 2545.19    80.5  2541.6    98.8 2535.36   134.9 2518.87
   148.7 2509.69   165.7 2501.67     177 2498.58   197.8 2500.07   218.1 2497.42
   238.4 2480.38   250.5 2465.98   270.8  2447.8   295.2 2429.87   315.5 2421.92
   336.3 2420.24     352 2419.12   360.32420.243   372.3 2425.69   380.4 2426.48
   392.6 2435.54   404.8 2440.83   510.3 2457.82   591.5 2483.16   615.8 2488.72
     632 2494.89   644.2 2496.27     701 2523.38   713.2 2526.62   718.5 2529.72
#Mann= 3 ,-1,0
       0      .1       0   336.3    .045       0   360.3      .1       0
Bank Sta=336.3,360.3
XS Rating Curve= 0 ,0
Exp/Cntr(USF)=0,0
Exp/Cntr=0.3,0.1

Type RM Length L Ch R = 1 ,9949    ,293.9,292.7,285.1
XS GIS Cut Line= 2
2252639.43187617659672.0111139632252538.99178714660390.847045233
#Sta/Elev= 30
       0 2559.82    13.3 2549.22    25.2 2546.31    33.5 2538.62    57.7 2524.88
    73.9 2516.77   110.2 2503.03   126.4 2492.02   150.6 2479.74   154.7 2478.58
   174.9 2478.96     187 2474.44   203.1 2461.27   211.2 2452.82   259.7 2419.55
   275.8 2409.95   289.72408.214     298 2407.32   316.52408.195   324.3 2411.45
   336.4 2413.66   348.5 2418.66   368.7 2419.84   388.9 2425.64   453.5 2437.19
   493.9  2457.1   554.5 2483.58   601.6 2500.36   635.3 2508.62   725.8 2550.77
#Mann= 3 ,-1,0
       0      .1       0   289.7    .045       0   316.5      .1       0
Bank Sta=289.7,316.5
XS Rating Curve= 0 ,0
Exp/Cntr(USF)=0,0
Exp/Cntr=0.3,0.1

Type RM Length L Ch R = 1 ,9656    ,331.1,328.5,318.5
XS GIS Cut Line= 3
2252259.33506868659620.8063626942252336.14219558659996.964343167
2252410.97990897660379.030564171
#Sta/Elev= 30
       0 2558.42     8.5 2552.09    24.9 2549.03      33 2542.33    86.1 2512.98
   147.4 2485.38   175.9 2464.15   196.3 2464.18   204.5 2461.89   208.6 2459.55
   220.8 2446.02     229 2439.19   265.7 2415.62     278 2409.54   290.2 2398.78
   306.6  2397.5   316.3 2398.56   371.9 2402.84   412.7 2402.07   437.1 2398.88
   445.3 2400.02     482 2425.42   518.6 2440.12     539 2452.03   551.3  2455.9
   612.4 2487.76   636.9 2493.72   647.7 2500.24   687.5 2514.44   773.2 2560.59
#Mann= 3 ,0,0
       0      .1       0   290.2    .045       0   316.3      .1       0
#XS Ineff= 2 , 0
                          380.33         2427.99
Permanent Ineff=
       F       F
Bank Sta=290.2,316.3
XS Rating Curve= 0 ,0
Exp/Cntr(USF)=0,0
Exp/Cntr=0.3,0.1

Type RM Length L Ch R = 1 ,9328    ,80.7,81,79.5
XS GIS Cut Line= 2
     2251802.867      659793.8412252362.28899637660426.240461588
#Sta/Elev= 30
       0 2546.83    36.5 2531.27    65.6 2510.92    80.5 2507.58   105.9 2492.26
   175.4 2463.85   207.3 2442.75   238.5 2439.05   276.8 2406.56   292.8 2396.43
   321.9 2394.32   356.9 2395.89   367.6 2392.59     400  2394.1   428.4 2391.69
   448.2 2389.24   462.4 2391.14   474.4 2395.47   493.5 2429.88   501.1 2437.63
   551.4 2459.03   581.5 2474.94   598.4 2479.22     660 2504.68   704.1 2519.49
   736.1 2538.21   773.5 2550.93   810.9 2569.91   821.5 2577.23   844.3 2587.21
#Mann= 3 ,-1,0
       0      .1       0   428.4    .045       0   462.4      .1       0
Bank Sta=428.4,462.4
XS Rating Curve= 0 ,0
Exp/Cntr=0.3,0.1

Type RM Length L Ch R = 1 ,9247    ,55.4,52.2,48.5
XS GIS Cut Line= 4
2251788.89591028659994.8399844972252016.94633368660153.671851199
2252100.99743824660250.7014351382252286.06517935660462.637485548
#Sta/Elev= 30
       0 2477.19    23.5 2468.48    55.8  2453.5      82 2436.13   104.6 2432.99
     119 2422.22   136.2 2405.98   159.2 2394.41   186.1 2392.29   257.5 2392.54
   279.9 2390.45     294 2391.88     311 2390.62   324.9 2389.65   333.7 2390.79
   340.8 2395.07   347.9 2401.79   367.8 2432.75   409.6 2452.69   420.2 2456.04
   441.5 2468.94   455.6 2472.96   464.2 2477.75   489.7 2484.51   531.7 2501.47
   543.5 2503.38   586.1 2519.62   625.7 2540.02   669.8 2553.35   687.6 2561.52
#Mann= 3 ,-1,0
       0      .1       0     311    .045       0   333.7      .1       0
Bank Sta=311,333.7
XS Rating Curve= 0 ,0
Exp/Cntr(USF)=0,0
Exp/Cntr=0.3,0.1

Type RM Length L Ch R = 1 ,9195    ,186.7,188.3,185
XS GIS Cut Line= 4
2251757.54385221660129.5042918612251982.39969637 660205.14384564
 2252047.6827455660250.5581406872252244.86465912660481.862516075
#Sta/Elev= 30
       0 2450.47    15.4 2448.26      45 2428.32    61.9 2428.34    70.3 2426.38
    87.2 2410.81    99.8 2401.59   112.5 2394.07   120.9 2391.29     142 2388.97
   150.5 2391.88   159.7 2392.16   184.2 2385.95   241.4 2387.79   255.72385.858
   267.3  2383.9   290.3 2385.83   301.8 2392.92   316.1 2408.99   321.8 2413.85
     336 2434.74   338.8 2437.62   351.7 2445.71   416.2 2471.43   434.7 2476.65
   446.4  2482.9   478.2 2493.49   490.2 2495.31   570.3 2527.12   620.7 2542.41
#Mann= 3 ,-1,0
       0      .1       0   255.7    .045       0   290.3      .1       0
Bank Sta=255.7,290.3
XS Rating Curve= 0 ,0
Exp/Cntr(USF)=0,0
Exp/Cntr=0.3,0.1

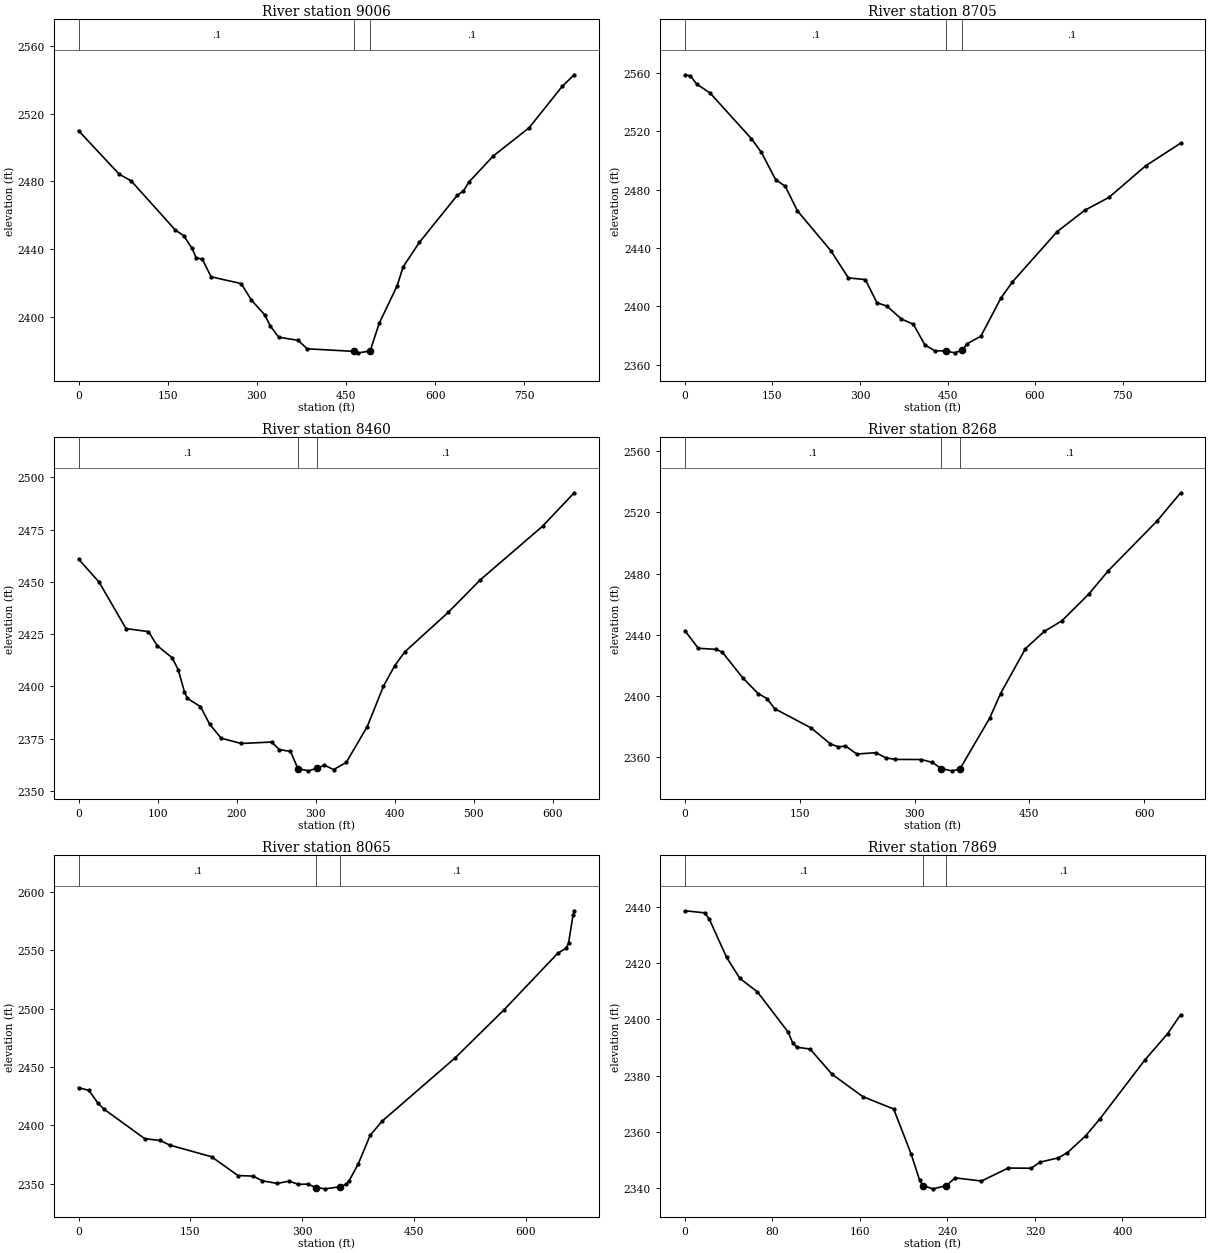
Type RM Length L Ch R = 1 ,9006    ,299.5,300.9,301.7
XS GIS Cut Line= 2
2251579.31486081660110.0240218742252240.15534878660618.429816199
#Sta/Elev= 30
       0 2509.92    68.5 2484.24    88.4  2480.4   162.6 2451.46   176.9 2448.03
   191.1 2440.54   197.9 2435.06   208.2 2434.24   223.1 2423.82   273.6 2419.84
     291 2410.04   313.5 2401.35   322.3 2395.03   336.6  2388.3   369.5 2386.38
   384.6 2381.43   463.82379.892   470.7 2379.04   490.6 2380.13   505.8 2396.41
     536 2418.53   546.1 2429.69   573.3 2444.06     637 2471.77   647.5 2474.38
   657.2  2479.8   697.5 2494.93   758.1 2511.64   813.6 2535.95   833.8 2542.82
#Mann= 3 ,-1,0
       0      .1       0   463.8    .045       0   490.6      .1       0
Bank Sta=463.8,490.6
XS Rating Curve= 0 ,0
Exp/Cntr(USF)=0,0
Exp/Cntr=0.3,0.1

Type RM Length L Ch R = 1 ,8705    ,247.8,245.5,243.4
XS GIS Cut Line= 2
2251437.30841776 660323.179277162252064.68060501 660895.99895635
#Sta/Elev= 30
       0  2558.6     9.3 2557.87    20.1 2552.21    43.1 2546.08   113.9 2514.84
   130.9 2505.52   155.5 2486.74   171.8 2482.32   192.8 2465.41   249.8 2438.26
   280.1 2419.54   309.2 2418.39     329 2402.54     346 2400.24   370.8 2391.44
   391.3 2387.87   411.2 2373.65   428.1  2369.7   447.9 2369.46   462.1 2368.24
   475.1    2370   483.5 2374.43   507.2 2379.68   541.4 2405.66   561.2 2416.78
   637.7 2451.15   685.2 2465.85   726.7 2474.67   789.3 2496.19   849.5 2511.79
#Mann= 3 ,-1,0
       0      .1       0   447.9    .045       0   475.1      .1       0
Bank Sta=447.9,475.1
XS Rating Curve= 0 ,0
Exp/Cntr=0.3,0.1

Type RM Length L Ch R = 1 ,8460    ,186.6,191.6,195.6
XS GIS Cut Line= 3
2251408.73368094660627.9986820242251494.06558618660731.265994004
 2251913.2907013660991.128137282
#Sta/Elev= 30
       0 2460.91      26 2449.92    60.1 2427.69    88.5 2426.22    99.6 2419.51
   118.4 2413.75   126.1 2408.08     134 2397.51   137.6 2394.33   154.3 2390.39
   165.9 2381.99   180.5 2375.26   205.9 2372.74   244.4 2373.43   254.1 2369.82
   268.2 2368.94   277.6 2360.76   290.9 2359.66   302.42360.971   311.2 2362.36
   322.8 2360.24   338.8 2363.69   365.4 2380.85   385.9 2400.15     400 2409.87
   412.9 2416.55   468.1 2435.53   508.2 2450.91   587.2 2476.62   627.2 2492.61
#Mann= 3 ,-1,0
       0      .1       0   277.6    .045       0   302.4      .1       0
Bank Sta=277.6,302.4
XS Rating Curve= 0 ,0
Exp/Cntr(USF)=0,0
Exp/Cntr=0.3,0.1

Type RM Length L Ch R = 1 ,8268    ,191.7,202.9,214
XS GIS Cut Line= 2
2251336.94855848660704.0909118262251720.11201724661226.210519632
#Sta/Elev= 30
       0 2442.67    17.4 2431.24      41 2430.52    48.9 2428.63    75.8 2411.75
    95.6  2401.7   106.9 2398.44   117.5 2391.71   165.1 2379.14   189.9 2368.81
   200.5 2366.84   209.7 2367.43   224.6 2362.18   249.4 2363.05   262.4 2359.74
   274.2 2358.68     309 2358.59   323.2  2356.7   334.82352.702   348.7 2351.21
   359.12352.311   398.3 2385.79   412.3 2401.67   444.9 2431.04   469.5 2442.28
   492.4 2449.16   527.3 2466.48   553.1 2481.88   616.6 2514.25   647.6 2532.78
#Mann= 3 ,-1,0
       0      .1       0   334.8    .045       0   359.1      .1       0
Bank Sta=334.8,359.1
XS Rating Curve= 0 ,0
Exp/Cntr=0.3,0.1

Type RM Length L Ch R = 1 ,8065    ,198.3,196.7,203.1
XS GIS Cut Line= 4
2251315.41302175660739.9834730532251378.73387935660953.427054312
2251351.61505531661191.1155708782251442.54287709661372.971214425
#Sta/Elev= 30
       0 2432.25    13.8 2430.01    26.3 2418.78    34.6 2413.64    88.9 2388.47
   109.7 2386.93   122.2 2383.03   178.6 2372.97     214 2356.84   234.5 2356.36
   246.5 2352.37   266.7 2350.09   282.8 2352.03   294.9 2349.31   307.8 2349.49
   318.92346.587   331.1 2345.44   351.32347.267   359.3 2349.41   363.3 2352.47
   375.4 2366.78   391.5 2391.49   407.6 2403.59   505.6 2457.91   571.2 2499.16
   643.1 2547.56   654.6 2552.06   657.6 2556.13   663.6 2580.04   665.2 2584.06
#Mann= 3 ,-1,0
       0      .1       0   318.9    .045       0   351.3      .1       0
Bank Sta=318.9,351.3
XS Rating Curve= 0 ,0
Exp/Cntr(USF)=0,0
Exp/Cntr=0.3,0.1

Type RM Length L Ch R = 1 ,7869    ,118.2,109.3,106.8
XS GIS Cut Line= 4
2251197.28342424660747.2050563722251206.35663444660847.810340576
2251189.57082924661029.402233143 2251236.1132891661192.682338225
#Sta/Elev= 30
       0 2438.57      18 2437.84    22.1 2435.69    38.1 2421.97    50.2 2414.51
    66.2 2409.75    94.4  2395.4    98.4 2391.69   102.4 2390.06   114.4 2389.42
   134.5 2380.44   162.6  2372.5   190.8  2368.1   206.8 2352.09   214.6 2342.69
  217.462340.883   226.9 2339.71     239 2340.85     247 2343.61   271.1 2342.49
   295.6 2347.11   316.4 2347.03   324.7 2349.19   341.4 2350.73   349.7 2352.57
   366.3 2358.53   379.2 2364.48   420.4 2385.48   441.2 2394.82   453.2 2401.65
#Mann= 3 ,0,0
       0      .1       0  217.46    .045       0     239      .1       0
Bank Sta=217.46,239
XS Rating Curve= 0 ,0
Exp/Cntr(USF)=0,0
Exp/Cntr=0.3,0.1

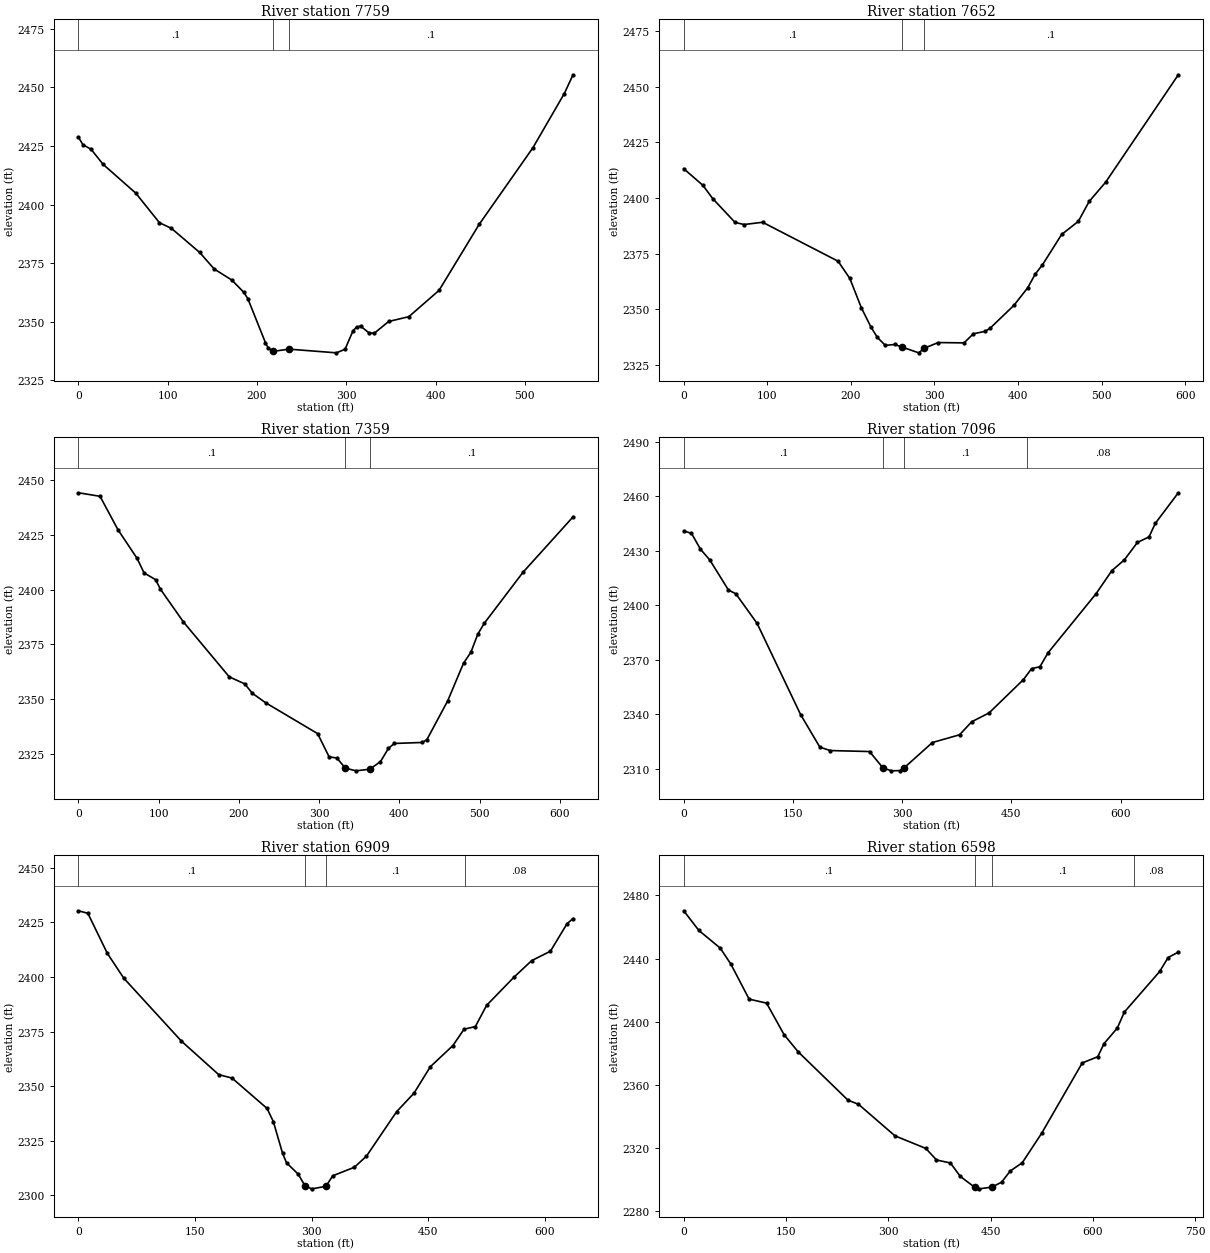
Type RM Length L Ch R = 1 ,7759    ,109.6,107.3,106.1
XS GIS Cut Line= 3
2250982.14341224660800.6993296252251179.04495356661180.130555854
2251255.42937342661280.984869916
#Sta/Elev= 30
       0 2428.72       5 2425.54    14.1 2423.59    27.6 2417.16    64.2 2404.87
    90.7 2392.26   104.2 2389.83   135.7  2379.6     152 2372.53   171.8 2367.79
   185.3 2362.54   189.8  2359.8   209.5 2341.03   212.5 2338.84   217.92337.367
   235.82338.322     289 2336.75   298.6 2338.27   307.5  2346.1   311.5 2347.74
     316 2348.14     325  2345.4   331.2 2345.05   347.5 2350.13   370.1 2352.18
   403.9 2363.39     449 2391.64   509.1 2424.26   544.2 2447.34     554 2455.36
#Mann= 3 ,-1,0
       0      .1       0   217.9    .045       0   235.8      .1       0
Bank Sta=217.9,235.8
XS Rating Curve= 0 ,0
Exp/Cntr=0.3,0.1

Type RM Length L Ch R = 1 ,7652    ,295.8,292.9,290.5
XS GIS Cut Line= 4
2250798.40221281660933.2720937732250980.58115399661043.980529965
2251088.73261947 661154.457833422251225.19347985661332.153305202
#Sta/Elev= 30
       0 2413.12    22.9 2405.66    34.8 2399.66    61.4 2389.02    72.3 2388.08
    94.4 2389.09   184.7 2371.61   198.7 2363.91   212.7 2350.57     224 2342.09
   231.6 2337.47   241.2 2333.83   252.6 2334.26   260.92333.125   281.2  2330.5
   287.6 2332.53   304.4 2335.11   335.4 2334.97   346.7 2339.08   360.4 2340.11
   366.5 2341.52     395 2351.77   411.6  2359.7   420.7  2365.9   429.1 2369.91
   452.2 2383.62   472.1 2389.48   485.1 2398.41   504.8 2407.05   591.8 2455.27
#Mann= 3 ,-1,0
       0      .1       0   260.9    .045       0   287.6      .1       0
Bank Sta=260.9,287.6
XS Rating Curve= 0 ,0
Exp/Cntr(USF)=0,0
Exp/Cntr=0.3,0.1

Type RM Length L Ch R = 1 ,7359    ,256.8,262.9,272
XS GIS Cut Line= 2
2250603.03182354661153.0637817032251118.20493334661491.473205976
#Sta/Elev= 30
       0 2444.22    26.9 2442.61    49.2 2427.36    73.1 2414.22    81.8  2407.6
    96.2 2404.49   102.2 2400.14   130.9 2385.16     188 2360.09   207.2  2356.9
   216.7  2352.6   233.3 2348.27   298.1 2334.16   312.4 2323.54     322 2323.04
   332.62318.423   345.9 2317.16   363.12317.917   376.4 2321.37   386.3  2327.4
   393.6 2329.67   428.4 2330.12   434.2 2331.38   460.2 2349.15   479.9 2366.33
   489.1 2371.35   497.7 2379.61   505.7 2384.55   553.9 2407.82   616.4  2433.2
#Mann= 3 ,-1,0
       0      .1       0   332.6    .045       0   363.1      .1       0
Bank Sta=332.6,363.1
XS Rating Curve= 0 ,0
Exp/Cntr=0.3,0.1

Type RM Length L Ch R = 1 ,7096    ,192.6,187.6,179.7
XS GIS Cut Line= 4
2250515.81289976661267.0298421112250598.12420162661331.510389492
2250711.91253778661550.3341128652250950.43039625661775.722547939
#Sta/Elev= 30
       0 2440.98    10.6 2439.68    22.9 2430.97    35.9 2424.94    61.4 2408.48
    71.6 2406.39   100.8 2390.09   160.5 2339.98     187 2322.02   201.1 2320.16
   255.2 2319.62   273.7 2310.61   285.3    2309   297.1 2309.15   303.1 2310.77
   341.6 2324.58   378.9 2328.83   395.6    2336   419.4 2340.85   466.6 2359.18
   477.9 2365.25   489.3 2366.28   500.5 2373.96   566.2 2406.34   588.2 2419.18
   605.2 2425.02   623.2 2434.64   639.2 2437.71   647.7 2445.09   679.4 2461.97
#Mann= 4 ,-1,0
       0      .1       0   273.7    .045       0   303.1      .1       0
   471.2     .08       0
Bank Sta=273.7,303.1
XS Rating Curve= 0 ,0
Exp/Cntr(USF)=0,0
Exp/Cntr=0.3,0.1

Type RM Length L Ch R = 1 ,6909    ,309.3,310.2,310.9
XS GIS Cut Line= 3
2250306.48748268661437.978932723      2250551.92      661623.425
2250824.27074253661807.947830776
#Sta/Elev= 30
       0 2430.29    12.1 2429.14    37.2 2410.77    58.4 2399.41   132.5 2370.63
   180.5  2355.3   197.7 2353.69   242.8  2339.8   250.8 2333.81   262.8 2319.19
   267.8 2314.92   282.9  2309.7   291.9  2304.2   300.5    2303   318.6 2304.15
   327.2 2308.95   355.1 2312.88   370.7 2317.96   409.4 2338.26     432 2346.85
   452.9 2358.89   481.9 2368.56   496.3 2376.06   510.9  2377.3   525.3 2386.98
   560.3  2399.8   583.3 2407.45   607.5 2411.78   628.8 2424.33   636.6 2426.75
#Mann= 4 ,-1,0
       0      .1       0   291.9    .045       0   318.6      .1       0
  497.62     .08       0
Bank Sta=291.9,318.6
XS Rating Curve= 0 ,0
Exp/Cntr=0.3,0.1

Type RM Length L Ch R = 1 ,6598    ,295.8,296.8,283.6
XS GIS Cut Line= 2
2250035.02697551661591.2094476212250592.97907799662054.745081768
#Sta/Elev= 30
       0 2470.27    22.1 2457.83    53.5 2446.62    69.1  2436.5    95.9 2414.27
   121.5 2411.76   147.1  2391.8   167.9 2380.86   240.9 2350.25   256.3 2347.65
   309.8 2327.65   355.1 2319.67   370.7 2312.36   391.2 2310.43   405.6 2301.94
   426.7 2295.08   433.1 2294.06   451.9 2295.13   466.3 2298.31   478.8 2305.33
   496.5 2310.59   524.9 2329.24   584.5 2373.85   607.2 2377.77   616.5 2386.11
   635.9 2395.95   646.3 2406.11   698.1 2431.81   710.4 2440.64   725.4 2444.06
#Mann= 4 ,-1,0
       0      .1       0   426.7    .045       0   451.9      .1       0
     660     .08       0
Bank Sta=426.7,451.9
XS Rating Curve= 0 ,0
Exp/Cntr=0.3,0.1

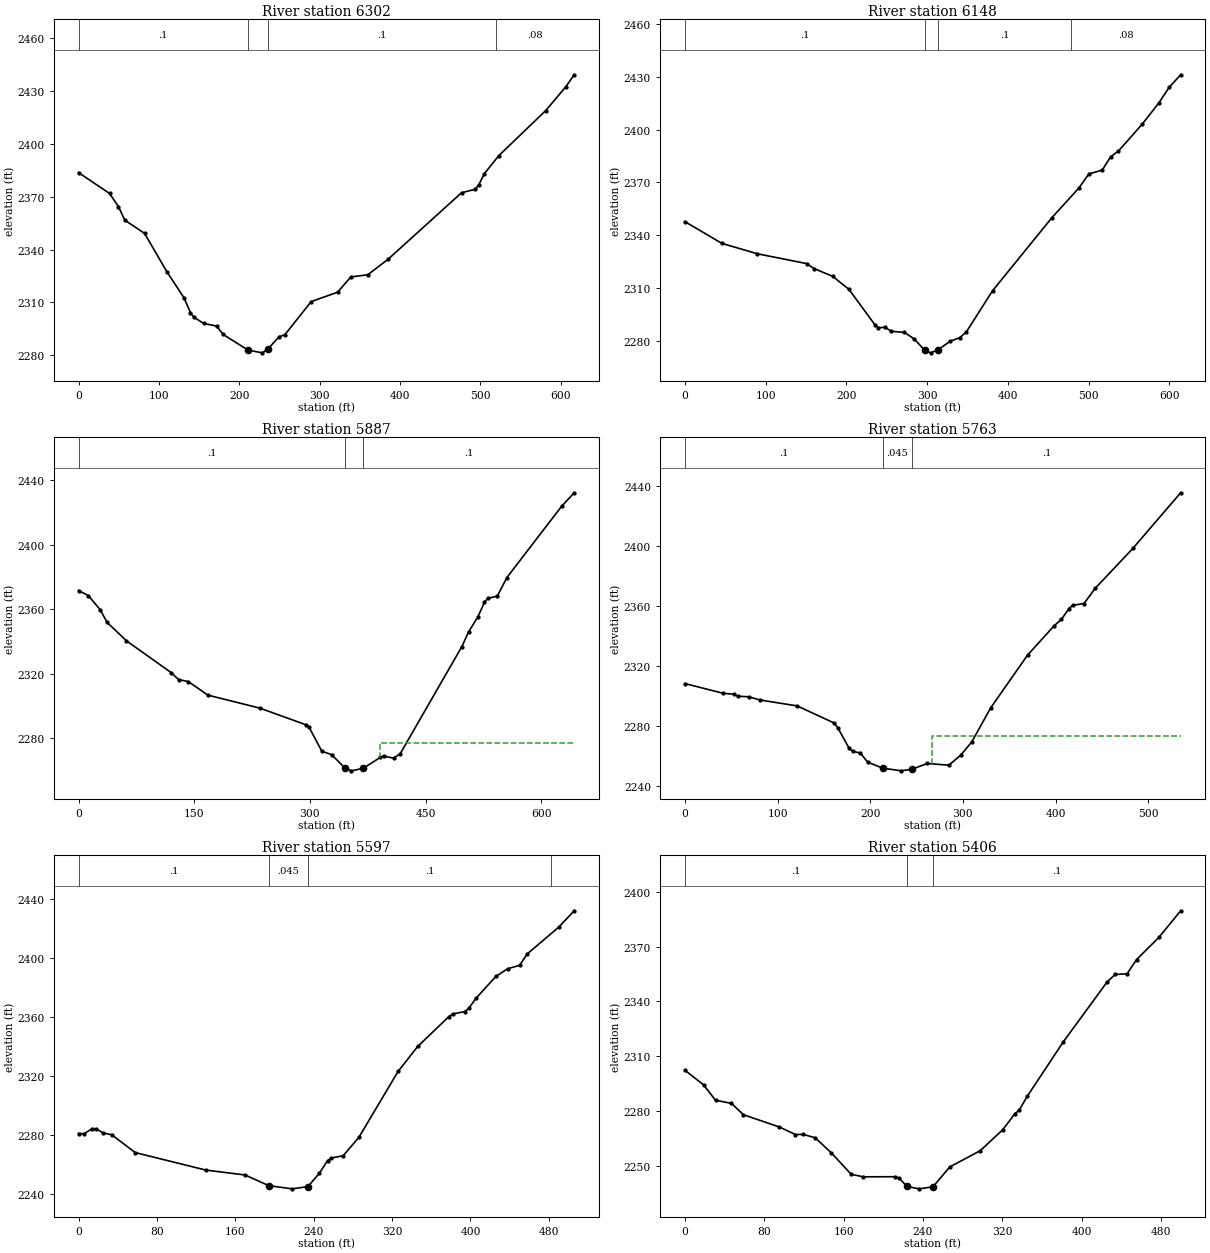
Type RM Length L Ch R = 1 ,6302    ,156.9,153.9,148.8
XS GIS Cut Line= 4
2249939.86615204661970.4191644662250070.33763787661998.649836839
2250244.29961898662028.406491503 2250538.0512099662117.676455494
#Sta/Elev= 30
       0 2383.62    38.6 2371.81    49.7 2364.37    57.6 2356.64    82.2 2349.15
   110.2 2327.24   131.3 2312.65   139.4 2304.12   143.5 2301.65   155.6 2298.11
   171.9 2296.57     180 2291.84     211 2282.95   228.7  2281.4   235.4 2283.35
     249 2290.26   257.1  2291.8   289.6 2310.46   322.4 2315.76   339.1 2324.47
     360 2325.65   385.1 2334.37   476.8  2372.2   493.8 2374.14     498 2376.51
   505.2    2383   523.1 2393.19   581.6 2418.79   606.7 2432.37     617 2439.09
#Mann= 4 ,-1,0
       0      .1       0     211    .045       0   235.4      .1       0
  519.98     .08       0
Bank Sta=211,235.4
XS Rating Curve= 0 ,0
Exp/Cntr(USF)=0,0
Exp/Cntr=0.3,0.1

Type RM Length L Ch R = 1 ,6148    ,257.6,260.8,264.2
XS GIS Cut Line= 4
 2249879.7221013662156.8235258962250037.34230736662183.903626379
2250293.20440662662146.4864682632250481.85570843662198.171756429
#Sta/Elev= 30
       0 2347.73    45.7 2335.38    89.7 2329.47   150.6 2323.91   159.9 2321.05
     183 2316.65   203.2 2309.22   235.8 2288.82   239.6 2287.44   247.7 2287.67
   255.8  2285.4   271.9 2284.77   284.1 2281.05     2972274.623   304.3 2273.16
   313.62274.914   328.5 2279.73   340.7 2281.86   348.7  2285.1   381.1 2308.48
   454.8 2350.09     488 2366.84   500.4 2374.86     517 2377.04   527.3 2384.57
   537.1  2387.9   566.8 2403.31   587.5 2415.45   599.9 2424.09   614.1 2431.22
#Mann= 4 ,-1,0
       0      .1       0     297    .045       0   313.6      .1       0
  478.51     .08       0
Bank Sta=297,313.6
XS Rating Curve= 0 ,0
Exp/Cntr(USF)=0,0
Exp/Cntr=0.3,0.1

Type RM Length L Ch R = 1 ,5887    ,127.7,124.4,118.6
XS GIS Cut Line= 4
2249765.25351634662271.9798073832250054.34238359662369.473120384
2250203.54954088662421.1869646722250375.64643252662472.900808959
#Sta/Elev= 30
       0 2371.63    12.7 2368.52    28.4 2359.53    36.9 2351.95    62.2 2340.42
   120.1 2320.71   129.7 2316.38   142.4 2315.16   167.7 2306.73   235.3 2298.64
   294.4 2288.41   298.6 2287.11   315.5 2271.94   328.2 2269.78   345.1 2261.66
   353.6 2259.75   369.2 2261.29   391.2 2268.08   395.9  2268.9   408.6 2267.61
   417.1 2270.34   497.1 2336.87   505.7 2345.84     518 2355.47   526.3 2364.22
   530.5 2366.75     543 2368.13   555.5  2379.7   626.5 2423.94   642.7 2432.28
#Mann= 3 ,-1,0
       0      .1       0   345.1    .045       0   369.2      .1       0
#XS Ineff= 2 , 0
                          390.56         2276.93
Permanent Ineff=
       F       F
Bank Sta=345.1,369.2
XS Rating Curve= 0 ,0
Exp/Cntr(USF)=0,0
Exp/Cntr=0.3,0.1

Type RM Length L Ch R = 1 ,5763    ,166.5,165.5,163.7
XS GIS Cut Line= 3
2249831.37941559662483.0740242292250180.65980652662505.963758586
2250362.92991343662537.331172334
#Sta/Elev= 30
       0 2308.06    40.9 2301.62    52.9 2300.93    56.9 2299.65    68.9 2299.23
      81 2297.11   121.1 2293.17   161.1 2281.74   165.1 2278.43   177.2  2264.9
   181.2  2262.8   189.2 2261.83   197.2 2255.66   213.3  2251.7   233.3 2249.87
   245.3 2251.01   261.4 2254.77   284.9 2253.65   297.4 2260.21   309.5 2269.11
     330 2291.87   369.8 2327.08   398.2 2346.44   406.4 2350.97   414.5  2358.1
   418.5 2360.22   430.7 2361.45   442.9 2371.66   483.5 2398.23     535 2435.29
#Mann= 3 ,-1,0
       0      .1       0   213.3    .045       0   245.3      .1       0
#XS Ineff= 2 , 0
                          266.93         2272.86
Permanent Ineff=
       F       F
Bank Sta=213.3,245.3
XS Rating Curve= 0 ,0
Exp/Cntr=0.3,0.1

Type RM Length L Ch R = 1 ,5597    ,191.4,190.6,190.2
XS GIS Cut Line= 3
2249862.33799871662670.8610188032250194.11878477662657.254866693
2250367.85888094662657.254866693
#Sta/Elev= 30
       0 2280.99     5.8 2280.92    13.8 2284.25    17.9 2284.28    25.2 2281.38
    33.9 2280.19    57.9  2268.1   129.9 2256.24     170  2252.9     194  2245.7
     218 2243.51   234.1 2245.01   245.7 2254.01   254.1 2262.63   258.1  2264.4
   270.1 2265.99   286.1 2278.42   326.1 2323.11   346.1 2340.05     378 2360.36
   382.1 2362.13   394.1 2363.75   398.1 2365.88     406 2373.03     426 2387.63
     438 2392.82   450.1 2395.09     458  2402.9   490.2 2421.08   505.8  2432.1
#Mann= 4 ,-1,0
       0      .1       0     194    .045       0   234.1      .1       0
  482.06     .08       0
Bank Sta=194,234.1
XS Rating Curve= 0 ,0
Exp/Cntr(USF)=0,0
Exp/Cntr=0.3,0.1

Type RM Length L Ch R = 1 ,5406    ,196.2,194.2,197.8
XS GIS Cut Line= 3
2249845.55320138662877.511722212     2250087.282      662851.284
2250341.73196777662816.781508617
#Sta/Elev= 30
       0  2302.4    18.7 2294.47    30.8 2286.05    46.9 2284.32      59 2278.11
    95.2 2271.43   111.3 2267.32   119.3 2267.37   131.4 2265.52   147.5 2257.36
   167.6 2245.62   179.7 2244.21   211.9 2244.27   215.9 2243.55   223.9 2238.98
     236 2237.65   250.12238.761   267.1 2249.62   297.8 2258.49   320.5 2269.95
   332.9 2278.77   336.9 2280.48   345.3 2288.27   381.3 2317.73   425.7 2350.62
   433.8 2354.72   445.9 2355.09   455.5  2362.9   478.2 2375.12   499.9 2389.52
#Mann= 3 ,-1,0
       0      .1       0   223.9    .045       0   250.1      .1       0
Bank Sta=223.9,250.1
XS Rating Curve= 0 ,0
Exp/Cntr=0.3,0.1

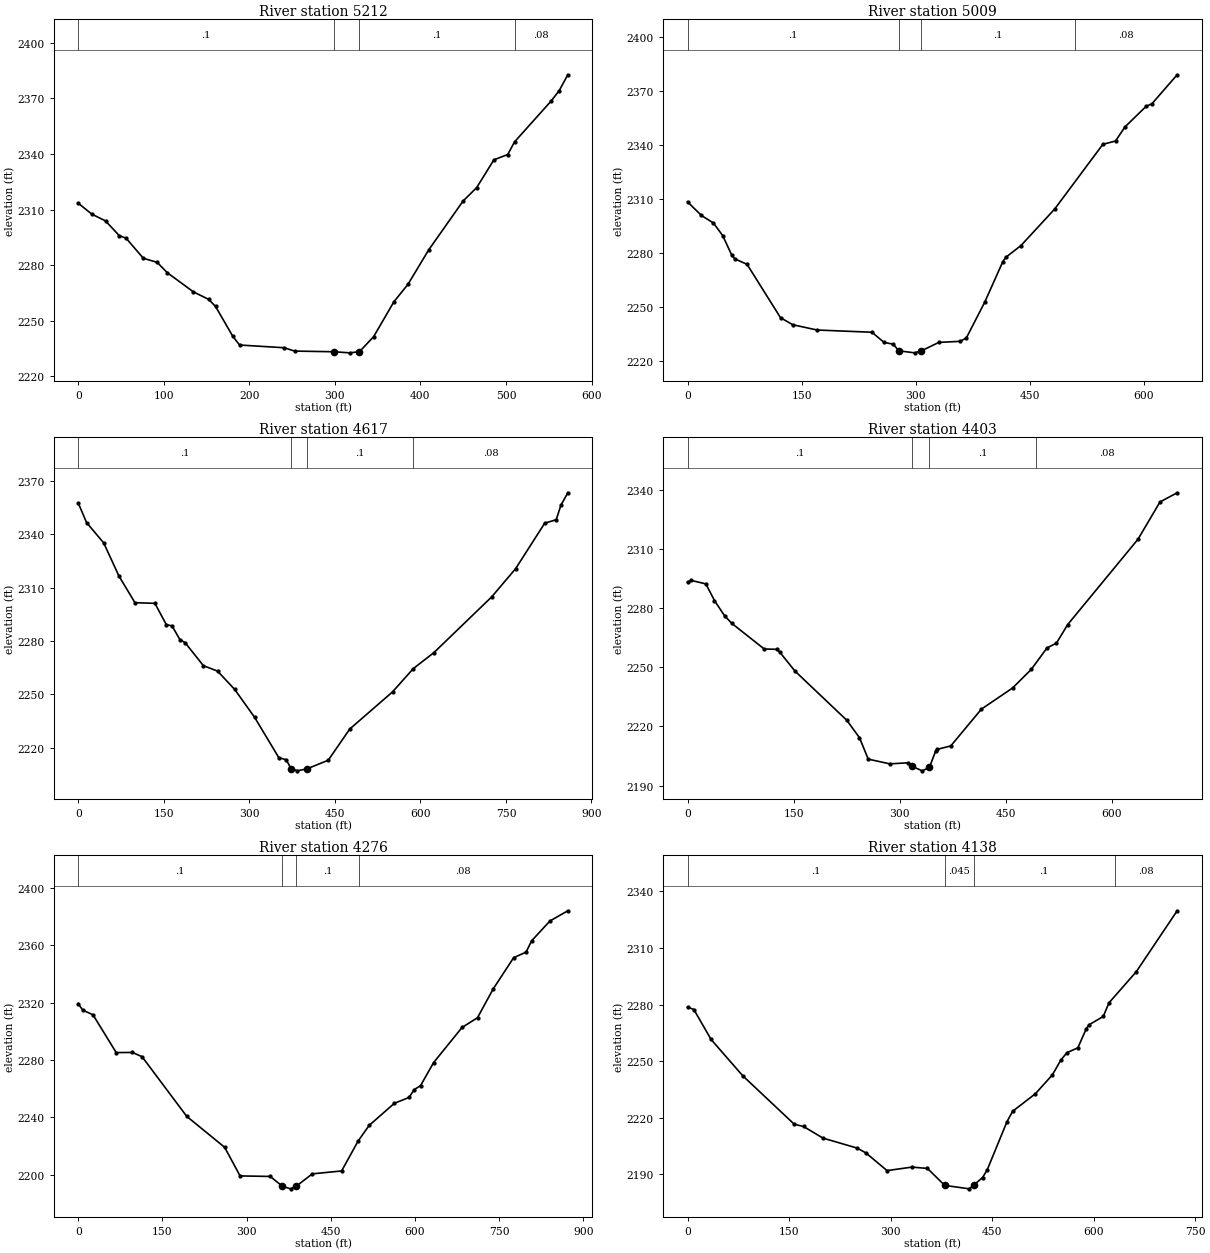
Type RM Length L Ch R = 1 ,5212    ,202.6,203.1,203.8
XS GIS Cut Line= 2
2249840.38807308663063.4178169492250410.21837511663009.923543697
#Sta/Elev= 30
       0 2313.44    15.9 2307.53    31.9 2303.87      48  2295.9      56 2294.52
    76.1  2283.7    92.2 2281.51   104.2 2275.88   134.7 2265.54   152.5  2261.5
   160.5  2257.7   180.6 2241.63   188.6 2236.86   240.8 2235.39   252.9 2233.59
   299.4 2233.22   317.2 2232.64   328.7 2233.25   345.3 2241.35   369.1 2260.27
   385.5 2269.65   409.5  2288.1   449.9 2314.61   465.8 2321.87   485.9 2336.85
     502 2339.68     510 2346.52   552.8 2368.59   562.2 2374.19   572.3 2382.76
#Mann= 4 ,-1,0
       0      .1       0   299.4    .045       0   328.7      .1       0
     510     .08       0
Bank Sta=299.4,328.7
XS Rating Curve= 0 ,0
Exp/Cntr(USF)=0,0
Exp/Cntr=0.3,0.1

Type RM Length L Ch R = 1 ,5009    ,406,391.7,391.3
XS GIS Cut Line= 3
2249838.06223512663244.8331784122250412.54421308663219.248960769
2250481.15643312663216.923122802
#Sta/Elev= 30
       0 2308.29    18.1 2300.77    34.1 2296.48    46.2 2289.54    58.2 2278.59
    62.2 2276.58    78.2 2273.56   122.2  2243.9   138.2 2239.98   170.3 2237.03
   242.4 2235.79   258.4 2230.12   270.4 2229.16   277.7 2225.48   298.4 2224.34
   306.72225.307   330.4 2230.15   358.5 2230.74   366.5 2232.59   390.5 2252.33
   414.5 2275.05   418.5 2277.47   438.4 2284.01   482.6 2304.26     546 2340.27
   562.7 2342.12   575.1 2349.96   602.7 2361.31   610.7 2362.91   643.7 2378.94
#Mann= 4 ,-1,0
       0      .1       0   277.7    .045       0   306.7      .1       0
     510     .08       0
Bank Sta=277.7,306.7
XS Rating Curve= 0 ,0
Exp/Cntr=0.3,0.1

Type RM Length L Ch R = 1 ,4617    ,210.9,214.3,217.2
XS GIS Cut Line= 3
 2249772.4933161663783.9615019542250202.77334007663461.832943467
2250520.25022262663414.153265135
#Sta/Elev= 30
       0 2357.71    14.6 2346.64    44.7 2335.18    71.4 2316.57    99.5 2301.58
   134.5 2301.21   154.5 2289.23   164.5 2288.54   178.2 2280.87   187.5 2279.06
   219.5 2266.17   244.4 2263.09   274.4 2252.78   309.4 2237.07   351.7 2214.45
   364.7 2213.26   373.2 2208.27   384.4 2207.02   401.8 2208.22   438.5    2213
   476.1 2230.52   551.1  2251.4   587.5 2264.49   623.7  2273.5     725 2304.83
   766.9 2320.68     818 2346.28   838.2 2348.23   846.3 2356.32   858.5 2363.38
#Mann= 4 ,-1,0
       0      .1       0   373.2    .045       0   401.8      .1       0
   587.5     .08       0
Bank Sta=373.2,401.8
XS Rating Curve= 0 ,0
Exp/Cntr(USF)=0,0
Exp/Cntr=0.3,0.1

Type RM Length L Ch R = 1 ,4403    ,128.7,127,125.8
XS GIS Cut Line= 3
2249891.86904129663854.702889172 2250291.6805879663689.335809685
2250526.12505502663576.300084466
#Sta/Elev= 30
       0 2293.26     4.7 2294.17    25.9 2292.37    38.1  2283.9    52.3 2276.23
    62.6 2272.33   108.5 2259.32   125.9 2259.15   130.2 2257.87   151.8 2248.19
   225.4 2223.12   243.3 2214.29   255.7 2203.41   286.2    2201     312 2201.54
     318 2199.72   332.1 2197.46   342.3 2199.21     351 2207.41   353.5 2208.37
   372.6 2210.13   415.9  2228.8   459.9 2239.49   486.5 2248.99   508.7 2259.86
     522 2262.26     538 2271.73   637.5 2315.05   668.6 2333.96   692.9 2338.62
#Mann= 4 ,-1,0
       0      .1       0     318    .045       0   342.3      .1       0
  492.66     .08       0
Bank Sta=318,342.3
XS Rating Curve= 0 ,0
Exp/Cntr(USF)=0,0
Exp/Cntr=0.3,0.1

Type RM Length L Ch R = 1 ,4276    ,138.9,138.3,134.1
XS GIS Cut Line= 3
2249909.24760028664033.8436816512250621.35601499663630.411293477
2250667.53188327663602.659956737
#Sta/Elev= 30
       0 2319.15       8 2314.75    26.4  2311.4    67.7 2285.13    96.5 2285.21
   113.7 2282.28   193.4 2240.67   260.9 2219.14   288.4  2199.2   342.2 2198.84
   363.6 2192.04   378.3  2190.2   387.8 2191.83   417.1 2200.64   469.3 2202.66
   498.6 2223.44   518.3 2234.37   563.2 2249.77   589.6  2253.9   598.4 2259.24
     610 2262.16   633.2 2278.16   683.8  2302.6   711.4 2309.43   739.2 2329.37
   775.7  2351.2   797.9 2355.11   807.9 2363.02   840.4 2376.79   872.3 2383.91
#Mann= 4 ,-1,0
       0      .1       0   363.6    .045       0   387.8      .1       0
     500     .08       0
Bank Sta=363.6,387.8
XS Rating Curve= 0 ,0
Exp/Cntr=0.3,0.1

Type RM Length L Ch R = 1 ,4138    ,139.7,157.2,165.7
XS GIS Cut Line= 4
2250007.35726534664106.8948718782250268.36797058664015.153485383
2250394.99692658 663867.850414112250636.62564876663794.198878474
#Sta/Elev= 30
       0 2278.69     9.3 2277.41    34.8 2261.51    81.4 2242.33   157.7 2216.56
   171.4 2215.37   200.1 2209.21     251 2203.88   263.7 2201.31   294.8 2191.98
   331.6 2193.84   354.5 2193.13     380 2184.14   416.4 2182.31   422.6 2184.21
   435.9 2188.28   442.8 2192.36   472.1 2217.98   480.4 2223.44     514 2232.74
   539.1 2242.74   551.6 2250.58   560.5 2254.49   576.7 2257.08   589.2 2267.21
   593.4 2269.33   614.3 2273.72   622.7 2280.93   663.1 2297.45   723.5 2329.76
#Mann= 4 ,-1,0
       0      .1       0     380    .045       0   422.6      .1       0
  630.91     .08       0
Bank Sta=380,422.6
XS Rating Curve= 0 ,0
Exp/Cntr(USF)=0,0
Exp/Cntr=0.3,0.1