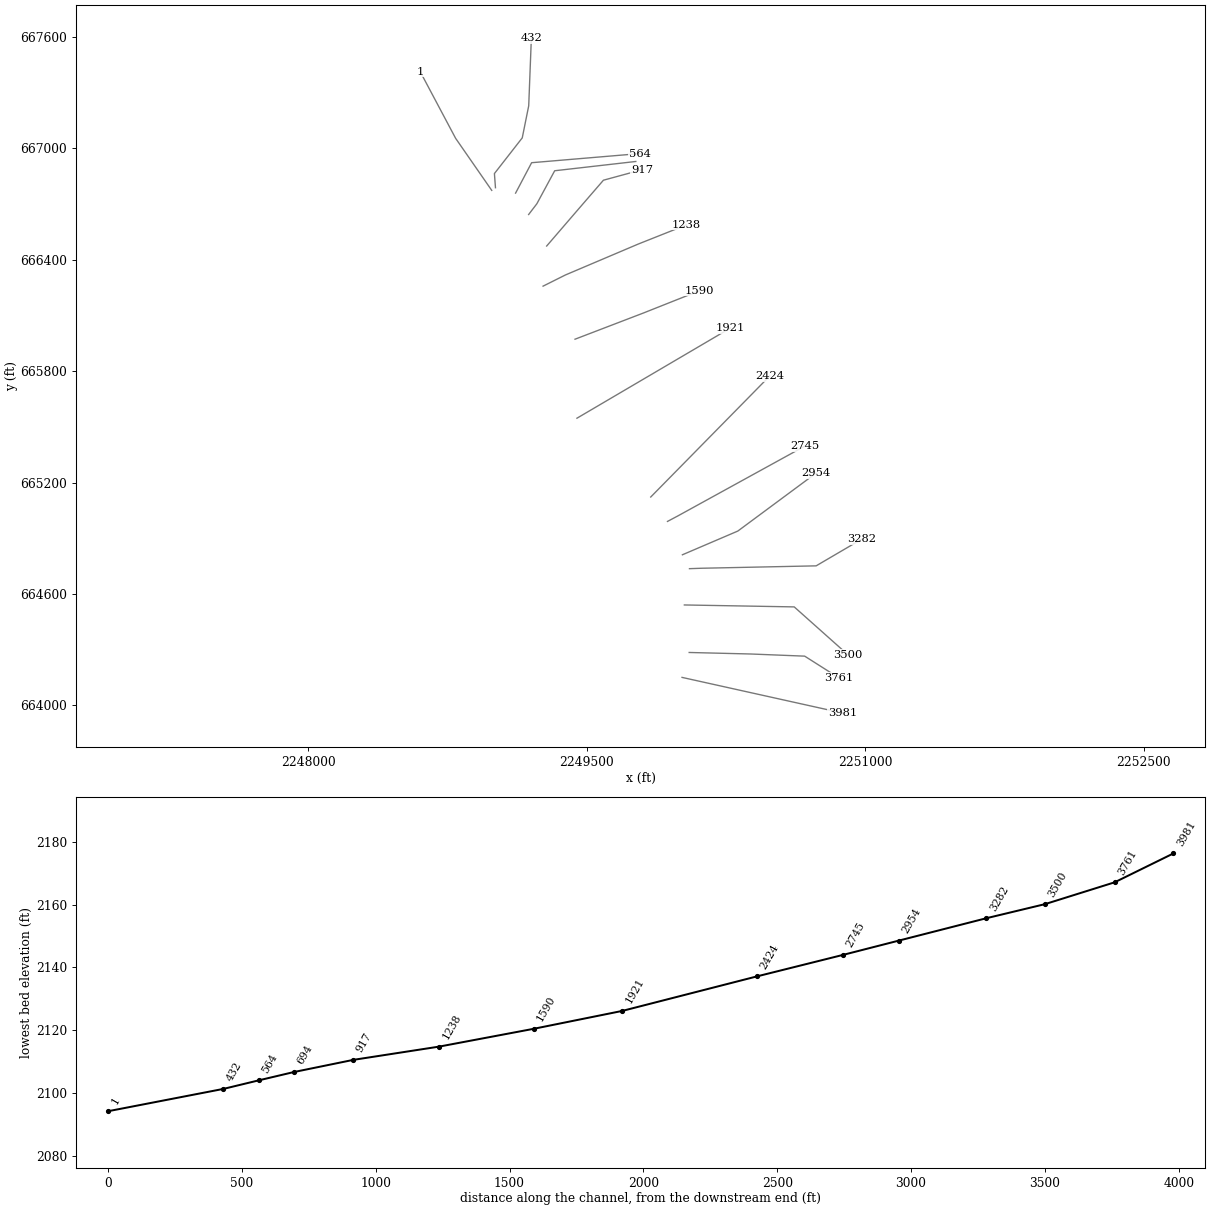
HEC-RAS study PANTHRN.prj: PANTHRN

--- PANTHRN.g01 (geometry) --- (continued)

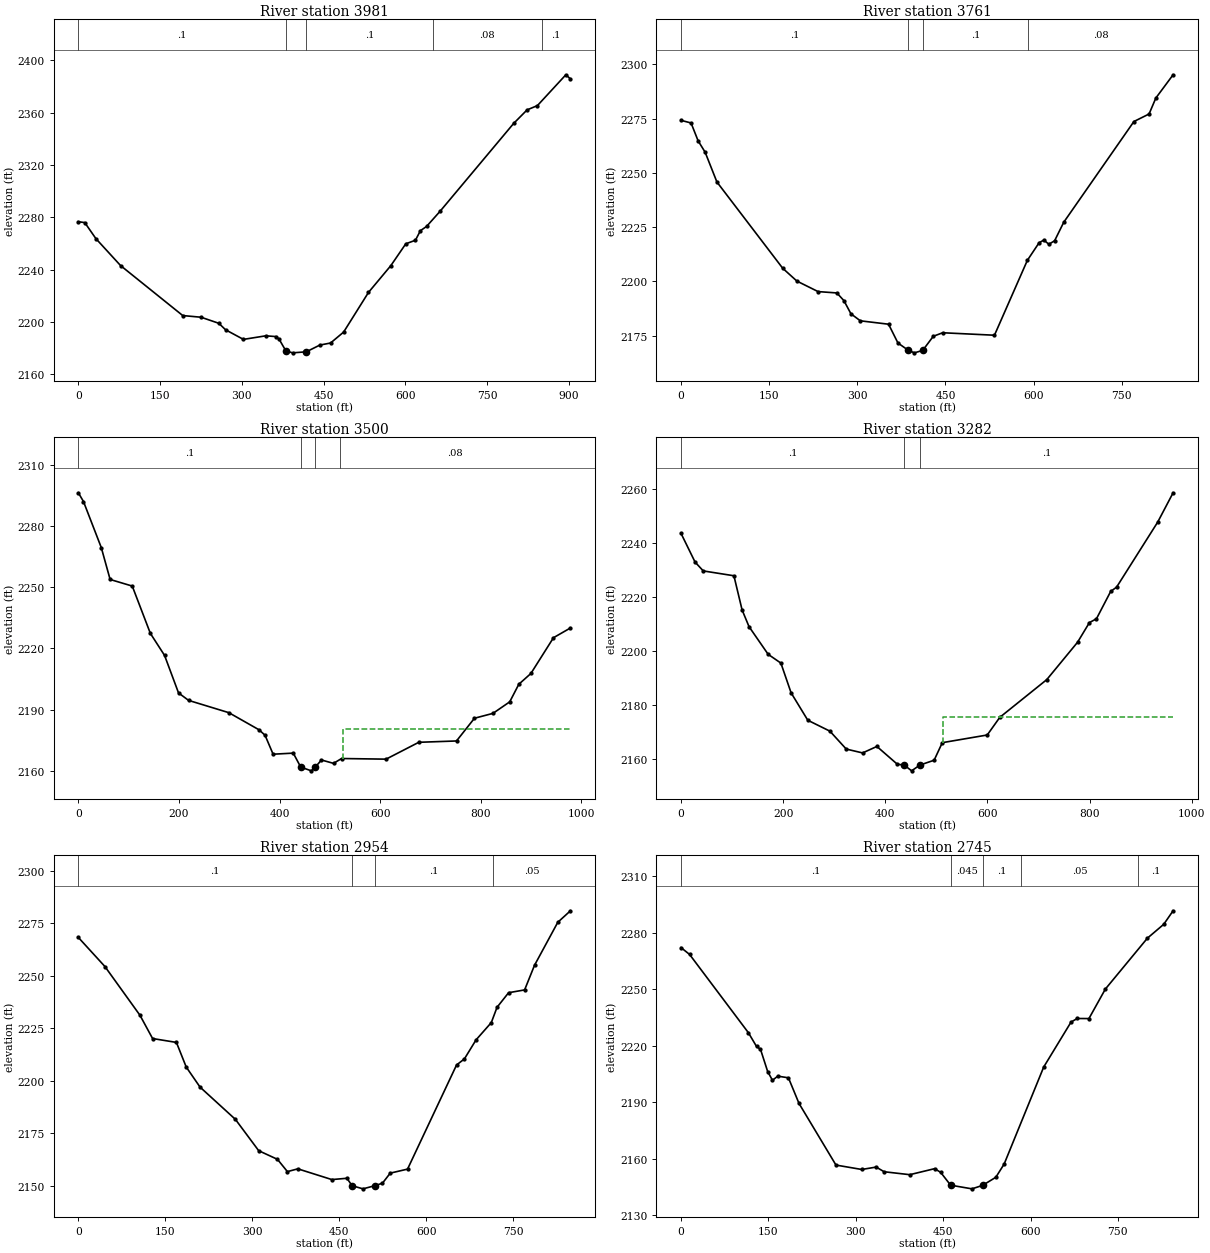
Type RM Length L Ch R = 1 ,3981    ,217,219.8,221.7
XS GIS Cut Line= 3
2250012.61817661664150.1355800222250885.52526561663956.315749404
     2250877.076      663956.333
#Sta/Elev= 30
       0 2276.57    11.8  2275.9    32.3 2263.59    77.5 2243.01   191.5 2204.78
   225.1  2203.5   257.7 2198.86     270 2193.92   302.8 2186.55   343.7 2189.27
   362.5 2188.71   368.3 2186.68   380.6 2177.79   392.9 2176.26   418.12177.034
     443 2182.21   462.6 2183.77   486.6 2192.14   532.2  2222.5   573.2 2242.98
   600.6 2259.68   618.3 2262.39   627.4  2269.7   638.7 2272.95   663.3 2284.46
   798.5 2351.79   823.1 2362.13     842 2365.39   894.2 2388.98   902.6 2385.82
#Mann= 5 ,-1,0
       0      .1       0   380.6    .045       0   418.1      .1       0
     650     .08       0     850      .1       0
Bank Sta=380.6,418.1
XS Rating Curve= 0 ,0
Exp/Cntr=0.3,0.1

Type RM Length L Ch R = 1 ,3761    ,260.3,260.8,261.3
XS GIS Cut Line= 4
2250051.07910316664284.3725891732250381.34809454664276.232156288
2250673.24075945 664264.602966452250854.65612091664149.473987064
#Sta/Elev= 30
       0 2274.25    17.1 2273.03    29.1 2264.81    41.1 2259.53    61.1 2245.82
   173.1 2206.04   197.2 2200.14   233.2  2195.3   265.2 2194.67   277.2 2191.14
   289.2 2185.05   305.2 2181.82   353.2 2180.26   369.2 2171.58     3872168.188
   397.2 2167.06   411.3 2168.18   429.3 2174.69   445.3 2176.32   533.4 2175.18
   589.4 2209.71   609.4 2217.83   617.4 2219.04     626 2217.12   635.8 2218.75
   651.3 2227.26   770.7  2273.7   796.5 2277.17     808 2284.52   837.4 2295.25
#Mann= 4 ,-1,0
       0      .1       0     387    .045       0   411.3      .1       0
  590.37     .08       0
Bank Sta=387,411.3
XS Rating Curve= 0 ,0
Exp/Cntr(USF)=0,0
Exp/Cntr=0.3,0.1

Type RM Length L Ch R = 1 ,3500    ,217,218,218.1
XS GIS Cut Line= 3
2250024.98600877664540.3519549342250616.91177147 664529.88568408
2250905.31567943664272.880588681
#Sta/Elev= 30
       0 2296.19    10.2 2291.92    45.6 2269.39    63.2 2253.76   107.2 2250.53
   143.2 2227.37   171.4  2216.6   199.2 2198.23   219.2 2194.58   299.2 2188.57
   359.2 2180.19   371.2 2177.52   387.2 2168.24   427.3 2168.77   442.12161.934
   463.3  2160.1   471.12161.927   483.3 2165.41   507.3 2163.76   523.3 2166.13
   611.8 2165.82   676.8 2174.07   751.8 2174.72   787.5 2185.84   824.3 2188.23
   857.6 2193.87   875.7 2202.48   899.7 2207.75   944.6 2225.26   978.3 2230.02
#Mann= 4 ,-1,0
       0      .1       0   442.1    .045       0   471.1      .1       0
     520     .08       0
#XS Ineff= 2 , 0
                          526.85         2180.58
Permanent Ineff=
       F       F
Bank Sta=442.1,471.1
XS Rating Curve= 0 ,0
Exp/Cntr(USF)=0,0
Exp/Cntr=0.3,0.1

Type RM Length L Ch R = 1 ,3282    ,317.8,328.3,339.8
XS GIS Cut Line= 4
 2250052.6494049664735.8458587762250117.65138062664738.084458761
 2250735.0034337664751.0057808022250977.63714758664893.140323255
#Sta/Elev= 30
       0 2243.56    27.5 2232.94    43.6 2229.65   103.6 2227.86   119.6 2215.23
   133.2 2209.02   170.7 2198.77   195.6 2195.53   215.6 2184.52   248.3 2174.37
   291.6 2170.33   323.6  2163.7   355.6 2162.27   383.6 2164.67   423.6 2158.09
   437.42157.745   451.6 2155.64   467.7 2157.77   495.7 2159.57   511.7 2166.07
   599.7 2168.91   624.3 2175.44   716.3 2189.41   776.6 2203.25   799.8 2210.52
   813.6 2211.94   841.5 2222.07     853 2223.64   933.5 2247.71   963.7 2258.58
#Mann= 3 ,-1,0
       0      .1       0   437.4    .045       0   467.7      .1       0
#XS Ineff= 2 , 0
                          512.72         2175.58
Permanent Ineff=
       F       F
Bank Sta=437.4,467.7
XS Rating Curve= 0 ,0
Exp/Cntr=0.3,0.1

Type RM Length L Ch R = 1 ,2954    ,208,208.6,204.4
XS GIS Cut Line= 3
2250014.49940919  664810.65997252250313.12551859664938.437490463
2250733.78633615  665249.9849219
#Sta/Elev= 30
       0 2268.16    45.9 2254.29   106.2 2231.13     128 2220.04   169.1 2218.19
     186 2206.46   209.8 2196.92   270.8 2181.55   310.9 2166.65   343.3 2162.53
   360.4 2156.69   378.4 2158.01     437  2152.9     463 2153.52   471.9 2149.98
   490.7 2148.49   510.9 2149.97   524.3 2151.19   537.7 2155.97   567.5 2157.88
     652 2207.45   665.5 2210.33   685.6  2219.4   711.9 2227.63   721.8 2234.92
   741.7 2241.85   769.3 2243.18   786.4 2254.92   826.5 2275.37   848.3 2280.85
#Mann= 4 ,-1,0
       0      .1       0   471.9    .045       0   510.9      .1       0
  714.81     .05       0
Bank Sta=471.9,510.9
XS Rating Curve= 0 ,0
Exp/Cntr(USF)=0,0
Exp/Cntr=0.3,0.1

Type RM Length L Ch R = 1 ,2745    ,316,321.1,326.4
XS GIS Cut Line= 3
2249934.16166286 664990.291600822249990.64740452665020.297694786
 2250674.8137551665396.473717553
#Sta/Elev= 30
       0 2272.11    14.7 2268.48   115.6 2226.92   129.6 2219.61   136.4 2218.11
   148.8 2206.22     157 2201.61   166.1 2203.81   184.4 2202.93   202.6 2189.29
     266 2156.57   310.2 2154.23     335  2155.5   348.7 2153.02   392.7 2151.46
   435.4 2154.66   445.7  2152.7   462.8 2145.88   499.4 2143.94   517.6 2145.77
   540.4 2150.08   554.7 2157.12   622.6 2208.67   669.5 2232.54   680.1 2234.44
   700.2  2234.4   728.4 2250.07   800.6 2277.12   828.6 2284.48   844.7 2291.67
#Mann= 5 ,-1,0
       0      .1       0   462.8    .045       0   517.6      .1       0
  583.96     .05       0  783.96      .1       0
Bank Sta=462.8,517.6
XS Rating Curve= 0 ,0
Exp/Cntr=0.3,0.1

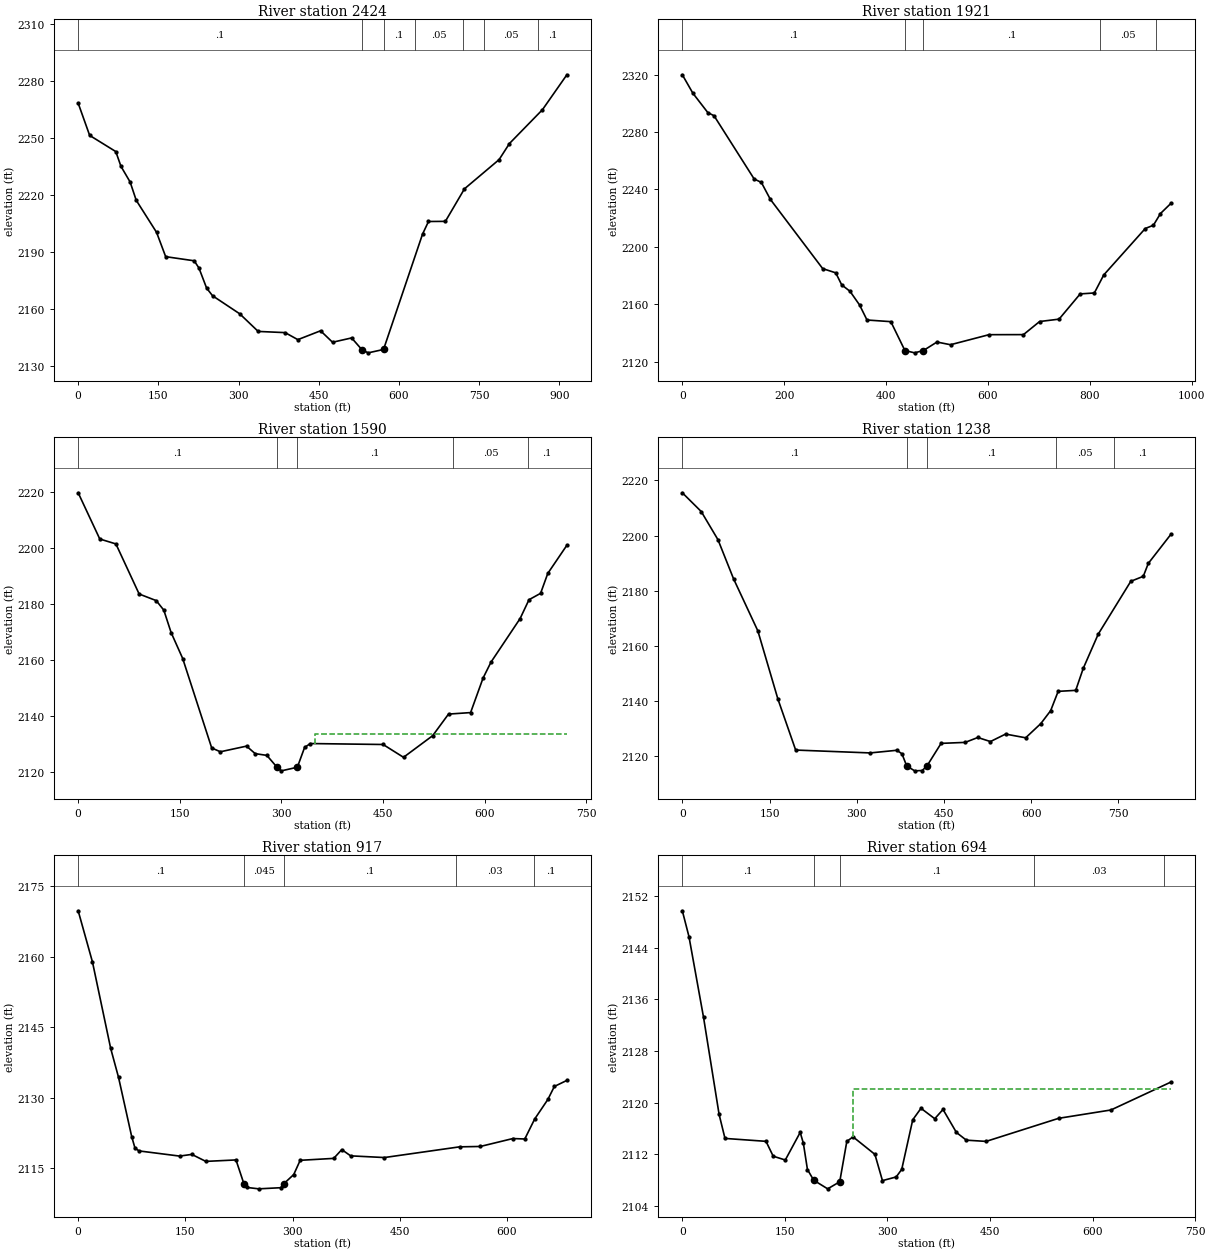
Type RM Length L Ch R = 1 ,2424    ,502.4,502.8,493
XS GIS Cut Line= 2
2249843.99656371665121.8506639352250485.09296382665773.794579822
#Sta/Elev= 30
       0 2268.53    21.5 2251.55    70.4 2243.04    80.1 2235.25    97.2 2227.03
   108.6 2217.41   146.7 2200.51   163.7 2187.73     217 2185.56   225.9  2181.8
   240.3 2171.19   251.4 2167.16   302.3 2157.64   336.8 2148.38   387.2 2147.75
     411 2144.05   453.5 2148.72   475.9 2142.68   511.6 2144.96   531.4 2138.59
   542.7 2137.11   571.3 2138.89   644.2 2199.54   655.4 2206.24     687 2206.31
   722.7 2223.43   787.5 2238.81   806.9 2247.29   868.6 2265.08   914.3 2283.46
#Mann= 7 ,-1,0
       0      .1       0   531.4    .045       0   571.3      .1       0
     630     .05       0     720      .1       0     760     .05       0
     860      .1       0
Bank Sta=531.4,571.3
XS Rating Curve= 0 ,0
Exp/Cntr=0.3,0.1

Type RM Length L Ch R = 1 ,1921    ,332.2,330.8,325.9
XS GIS Cut Line= 2
     2249446.497      665546.3782250274.01642313666032.579726076
#Sta/Elev= 30
       0 2319.89    20.8    2307      50 2293.58    62.3 2291.33   141.1 2247.27
   155.2 2244.89   172.8 2233.12   275.7 2184.81   301.3 2181.88     313  2173.5
   329.3 2169.01   348.1 2159.48   362.7 2149.01   409.5 2147.86   437.12127.752
   456.2 2126.13   473.52127.745   500.1 2133.66   526.7 2131.78   602.3 2138.78
     670 2138.83   701.7 2147.95   739.9 2149.61   781.4  2167.2   809.2 2167.85
   827.7 2180.43   909.2 2212.77   925.2 2215.05   939.1 2223.22   959.8 2230.36
#Mann= 5 ,-1,0
       0      .1       0   437.1    .045       0   473.5      .1       0
     820     .05       0     930      .1       0
Bank Sta=437.1,473.5
XS Rating Curve= 0 ,0
Exp/Cntr=0.3,0.1

Type RM Length L Ch R = 1 ,1590    ,352.8,352.8,354.7
XS GIS Cut Line= 3
2249436.11926362665971.9827175982249803.60166247666112.695914627
 2250108.2864362666233.639488932
#Sta/Elev= 30
       0 2219.77    31.9 2203.26    55.7  2201.5      90 2183.61   115.2 2181.25
   126.4 2177.85   137.2 2169.83   154.3 2160.56   197.1 2128.61   209.9 2127.25
   248.5 2129.27   261.3 2126.58   278.5 2125.96   293.5 2121.72   299.9 2120.44
   323.52121.726   334.2 2128.81   342.7 2130.19   450.1 2129.85   480.2 2125.27
   523.2    2133   546.6 2140.71   579.2 2141.25   597.6 2153.58   609.3 2159.27
   652.3 2174.85   665.4 2181.57   682.5 2183.85   693.1 2190.95   721.3 2201.02
#Mann= 5 ,-1,0
       0      .1       0   293.5    .045       0   323.5      .1       0
   553.5     .05       0   663.5      .1       0
#XS Ineff= 2 , 0
                          349.12         2133.57
Permanent Ineff=
       F       F
Bank Sta=293.5,323.5
XS Rating Curve= 0 ,0
Exp/Cntr(USF)=0,0
Exp/Cntr=0.3,0.1

Type RM Length L Ch R = 1 ,1238    ,309.6,320.6,330.2
XS GIS Cut Line= 4
2249263.98852053666257.7502045142249384.56038628666318.058139022
2249778.25713777666485.1654724392250036.50093555666587.710400129
#Sta/Elev= 30
       0 2215.53    32.5 2208.74    61.3 2198.53    88.1 2184.36   129.9 2165.48
   164.4 2140.77   194.9 2122.31     323 2121.27     369 2122.23   377.7 2120.94
   385.82116.572   399.5 2114.78   412.5  2114.9   420.72116.558     445 2124.73
   486.4 2125.09   508.1 2126.86   529.8 2125.39   555.9  2128.1   590.4 2126.75
   616.4 2131.88   633.4 2136.59   646.3 2143.58   676.5 2143.94   689.4 2151.89
   715.2 2164.31   771.2 2183.45   792.7 2185.26   801.3 2189.94   840.4 2200.54
#Mann= 5 ,-1,0
       0      .1       0   385.8    .045       0   420.7      .1       0
  642.51     .05       0  742.51      .1       0
Bank Sta=385.8,420.7
XS Rating Curve= 0 ,0
Exp/Cntr=0.3,0.1

Type RM Length L Ch R = 1 ,917     ,217.5,222.9,224.4
XS GIS Cut Line= 4
2249283.32264685666473.850010174     2249455.399      666673.743
2249589.12726849666828.4685150822249797.00099061666884.962457547
#Sta/Elev= 30
       0 2169.82      20 2158.91    45.5 2140.48    56.5  2134.3    74.9 2121.68
    79.5 2119.24    85.2 2118.64   141.9 2117.54     159  2117.9   178.6 2116.41
   220.8 2116.72   231.82111.671   236.6 2110.85   252.5 2110.56   283.3  2110.8
   287.72111.653   301.6 2113.61   310.6 2116.64   357.5 2117.05   368.8 2118.92
   381.2 2117.59   428.4 2117.23   533.6 2119.51   562.6 2119.59   608.2 2121.28
   624.8 2121.18   638.7 2125.45   657.1 2129.61   666.2 2132.38   683.7 2133.67
#Mann= 5 ,-1,0
       0      .1       0   231.8    .045       0   287.7      .1       0
  528.26     .03       0  638.26      .1       0
Bank Sta=231.8,287.7
XS Rating Curve= 0 ,0
Exp/Cntr=0.3,0.1

Type RM Length L Ch R = 1 ,694     ,129.8,130.5,130.2
XS GIS Cut Line= 4
2249186.26285416666643.6580801212249230.51634059666701.645407157
2249326.54042653666879.3768629622249763.54540744666929.325447644
#Sta/Elev= 30
       0 2149.69     9.7  2145.7      31 2133.22    53.8 2118.18    62.4 2114.47
   122.4 2114.02   132.9 2111.72   150.6 2111.13   172.4  2115.4     177 2113.74
     183 2109.66   192.22107.998   212.6 2106.67   230.2 2107.76   240.6 2114.01
   249.7 2114.71   281.7    2112   292.7 2107.94   312.8 2108.51   320.9 2109.68
     337 2117.35   349.1 2119.13   369.2 2117.52   381.3 2118.95   400.9 2115.39
   415.4  2114.2   444.3 2114.01   550.4 2117.58   626.9 2118.87   714.8  2123.2
#Mann= 5 ,-1,0
       0      .1       0   192.2    .045       0   230.2      .1       0
  514.96     .03       0  704.96      .1       0
#XS Ineff= 2 , 0
                          249.81         2122.05
Permanent Ineff=
       F       F
Bank Sta=192.2,230.2
XS Rating Curve= 0 ,0
Exp/Cntr(USF)=0,0
Exp/Cntr=0.3,0.1

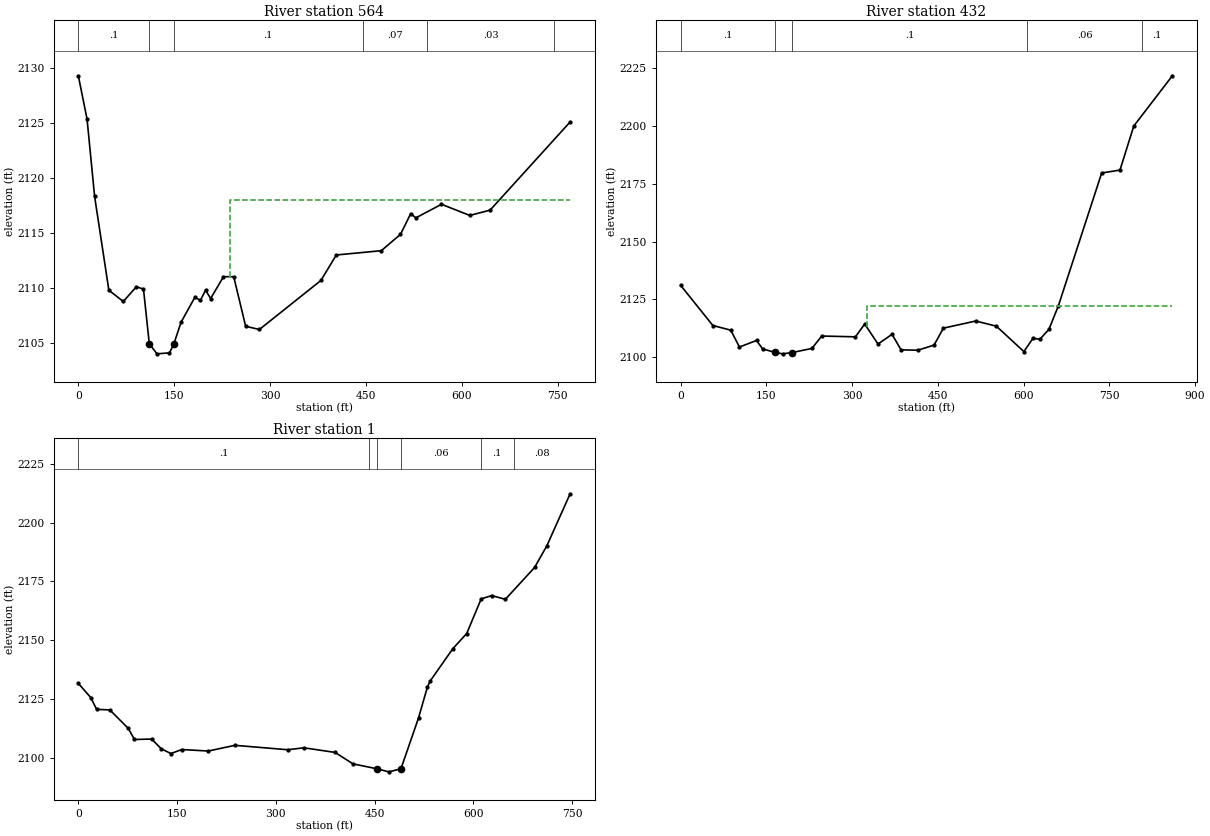
Type RM Length L Ch R = 1 ,564     ,135.6,132,129.4
XS GIS Cut Line= 3
 2249115.9414139666758.929208788 2249202.2923781666922.719798219
2249784.73915348666971.908871006
#Sta/Elev= 30
       0 2129.27    13.7 2125.33    25.5 2118.32    47.8 2109.81    70.4 2108.79
    90.9 2110.13     102 2109.91   111.1 2104.95   123.2 2104.04   142.7 2104.13
   149.22104.889   160.8 2106.91   182.5 2109.18   191.1 2108.89   199.1 2109.82
   207.1 2109.06   227.2 2111.04   243.2 2111.04   261.9 2106.54   283.4 2106.25
   379.7  2110.7   403.8 2113.01   474.2  2113.4   504.2 2114.88   520.2 2116.76
   528.3 2116.38   568.4 2117.61   612.6  2116.6   644.5 2117.08   769.7 2125.08
#Mann= 6 ,-1,0
       0      .1       0   111.1    .045       0   149.2      .1       0
  445.16     .07       0  545.16     .03       0  745.16      .1       0
#XS Ineff= 2 , 0
                          236.93            2118
Permanent Ineff=
       F       F
Bank Sta=111.1,149.2
XS Rating Curve= 0 ,0
Exp/Cntr(USF)=0,0
Exp/Cntr=0.3,0.1

Type RM Length L Ch R = 1 ,432     ,403.4,431.2,446
XS GIS Cut Line= 5
2249007.54973137666788.0040923492249001.88521278666864.290219832
 2249151.8139618667056.4551023222249186.64948328667229.418632083
2249200.80312071667592.692548849
#Sta/Elev= 30
       0 2131.05    56.5  2113.6    87.8 2111.58     103 2104.28   132.9 2107.11
   143.6 2103.46  165.392101.932   178.5 2101.32   195.6  2101.9   229.8 2103.66
   246.9 2109.04   305.9 2108.69   322.1 2114.25   345.4 2105.58   369.9 2109.78
   385.7 2103.05   414.8 2102.89   443.4 2105.09   459.7 2112.45   516.4 2115.55
   552.5 2113.29   600.5 2102.31   616.5 2108.08   628.5 2107.63   644.3 2111.95
   660.6 2121.94   736.6  2179.7   768.6 2180.96   792.7 2200.03   860.2 2221.83
#Mann= 5 ,-1,0
       0      .1       0  165.39    .045       0   195.6      .1       0
  606.67     .06       0  806.67      .1       0
#XS Ineff= 2 , 0
                          325.42         2121.98
Permanent Ineff=
       F       F
Bank Sta=165.39,195.6
XS Rating Curve= 0 ,0
Exp/Cntr=0.3,0.1

Type RM Length L Ch R = 1 ,1       ,,,
XS GIS Cut Line= 3
2248987.35181014666773.654393358 2248792.8001628667054.220399501
  2248602.439804667412.481775581
#Sta/Elev= 30
       0 2131.75    18.9 2125.73    27.8 2120.73    47.9 2120.48    75.8 2112.67
    85.3 2107.94   111.4 2108.12     126 2103.99   140.6 2101.98   157.2 2103.68
   197.4 2103.04   237.9 2105.46   318.1 2103.59   342.8 2104.41   390.1 2102.45
   417.2  2097.6  453.912095.489   471.6 2094.21  490.11 2095.49   516.9 2117.16
   530.4 2130.31     535 2132.95   568.9 2146.46     590 2152.91     612 2167.59
     628 2169.01   648.7 2167.42   693.1 2180.92   711.7 2190.09   747.1  2212.2
#Mann= 6 ,-1,0
       0      .1       0  441.42     .06       0  453.91    .045       0
  490.11     .06       0  611.42      .1       0  661.42     .08       0
Bank Sta=453.91,490.11
XS Rating Curve= 0 ,0
Exp/Cntr=0.3,0.1
LCMann Table=0

Chan Stop Cuts=-1
Use User Specified Reach Order=0
Composite Channel Slope=5